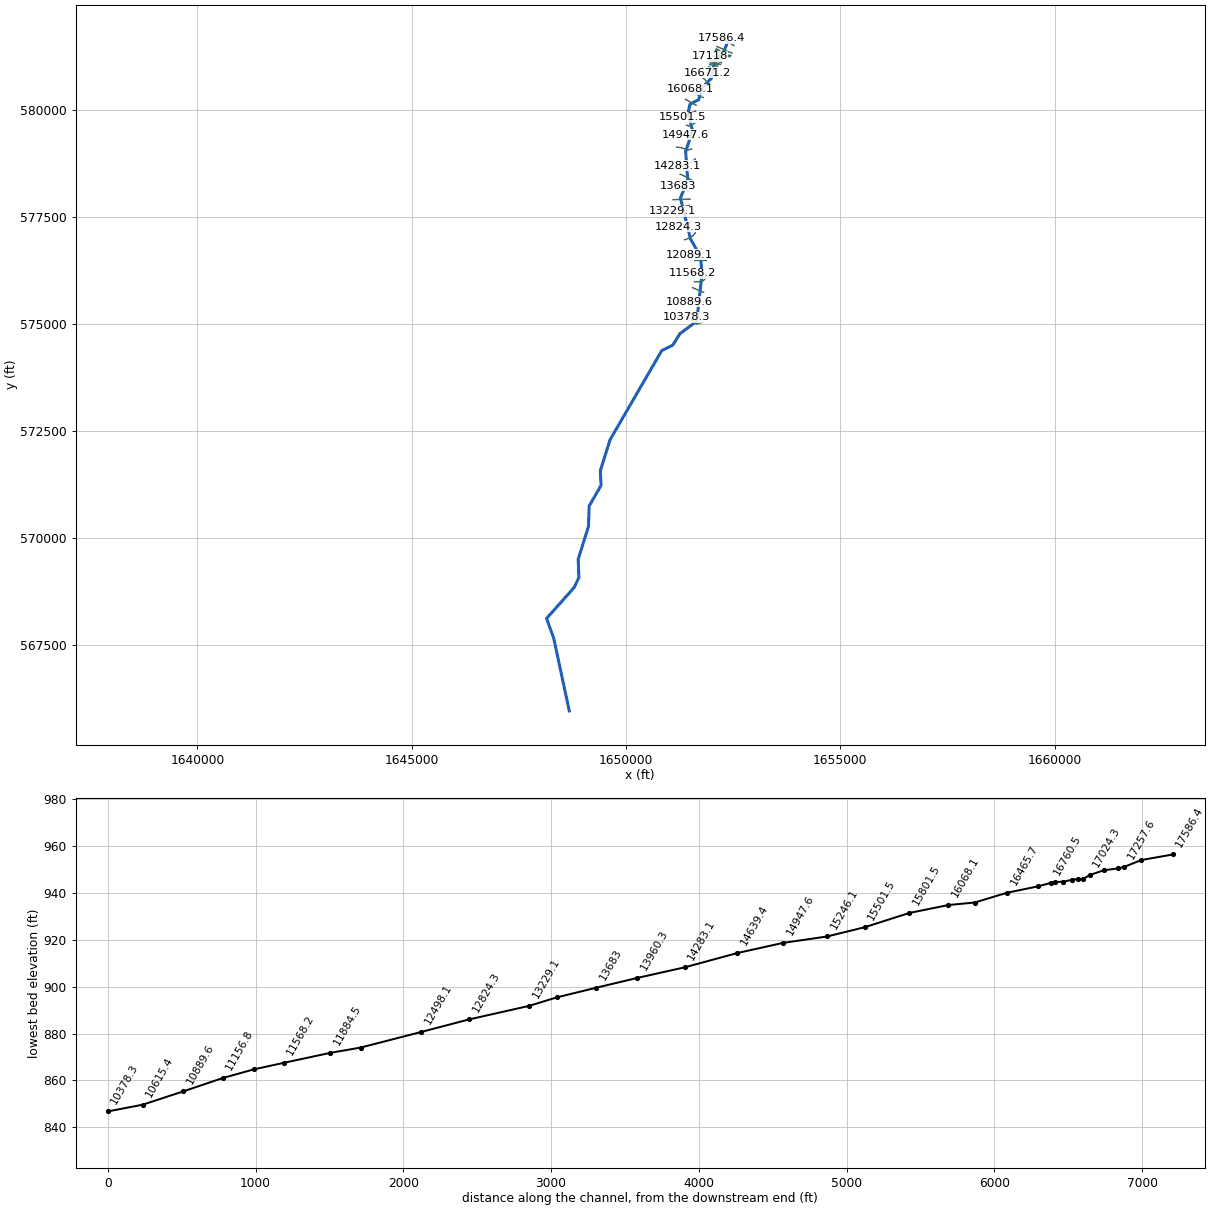
--- PETERSRUN.prj (project) ---

Proj Title=PETERSRUN
Current Plan=p01
Default Exp/Contr=0,0
English Units
Geom File=g01
Flow File=f01
Plan File=p01
BEGIN DESCRIPTION:
END DESCRIPTION:
DSS Export Rating Curves= 0
DSS Export Rating Curve Sorted= 0
DSS Export Volume Flow Curves= 0
DXF OffsetX= 0
DXF OffsetY= 0
DXF ScaleX= 0
DXF ScaleY= 0

--- PETERSRUN.p01 (plan) ---

Plan Title=Floodplain
Program Version=4.00
Geom File=g01
Flow File=f01
K Sum by GR=0
Std Step Tol=0.01
Critical Tol=0.01
Num of Std Step Trials=20
Max Error Tol=0.3
Flow Tol Ratio=0.001
Split Flow NTrial=30
Split Flow Tol=0.02
Split Flow Ratio=0.02
Log Output Level=0
Friction Slope Method=1
Unsteady Friction Slope Method=2
Unsteady Bridges Friction Slope Method=1
Global Log Level=0
CheckData=False
Run HTab=0
Run UNet=0
Run PostProcess=0
UNET Theta=0
UNET Theta Warmup=0
UNET ZTol=0
UNET ZSATol=0
UNET MxIter=0
UNET MaxInSteps=0
UNET DtIC=0
UNET DtMin=0
UNET MaxCRTS=0
UNET WFStab=0
UNET SFStab=0
UNET WFX=0
UNET SFX=0
UNET DSS MLevel=0
UNET DZMax Abort=0
UNET Convert EG Bridges=0
UNET Use Existing IB Tables=0
UNET Froude Limit=0
UNET Froude Power=0
Write IC File=0
Echo Input=False
Echo Output=False
Write Detailed=0

--- PETERSRUN.f01 (steady flow) ---

Flow Title=NFF Regression Equation
Program Version=4.10
Number of Profiles= 1
Profile Names=P100yr
River Rch & RM=PETERSRUN,Main            ,17586.4
926.2377
River Rch & RM=PETERSRUN,Main            ,16465.7
945.6233
River Rch & RM=PETERSRUN,Main            ,16068.1
1050.997
River Rch & RM=PETERSRUN,Main            ,13960.3
 1157.26
River Rch & RM=PETERSRUN,Main            ,11156.8
1253.359
River Rch & RM=PETERSRUN,Main            ,7546.7
 1352.31
River Rch & RM=PETERSRUN,Main            ,7223.7
1675.706
River Rch & RM=PETERSRUN,Main            ,5254.1
1783.996
River Rch & RM=PETERSRUN,Main            ,664.3
1905.923
Boundary for River Rch & Prof#=PETERSRUN,Main            , 1
Up Type= 0
Dn Type= 3
Dn Slope=0.013
DSS Import GetInterval= 0
DSS Import GetPeak= 0
DSS Import FillOption= 0

--- PETERSRUN.g01 (geometry) ---

Geom Title=USGS 10m DEM
Program Version=4.10

River Reach=PETERSRUN       ,Main
Reach XY= 30
     1652377.275      581619.336     1652269.473       581342.06
     1652074.161      581182.555      1651990.61      580747.442
     1651769.256      580525.003     1651694.386       580248.31
     1651493.649      580145.229     1651446.991      579942.321
     1651552.242      579525.654     1651391.192      579035.601
     1651440.224      578367.093     1651270.117      577951.255
     1651502.329      576996.357     1651739.959      576576.435
     1651771.426      576171.704     1651650.054      575069.097
     1651257.693      574776.562     1651091.088      574509.378
     1650830.671         574377.     1649625.749      572292.187
     1649399.465       571568.84     1649418.996      571230.298
     1649140.505      570747.916     1649124.012      570267.881
      1648883.84      569501.349     1648900.705      569071.267
     1648786.449      568836.052     1648145.992      568115.932
       1648314.1       567651.13     1648676.096      565953.862

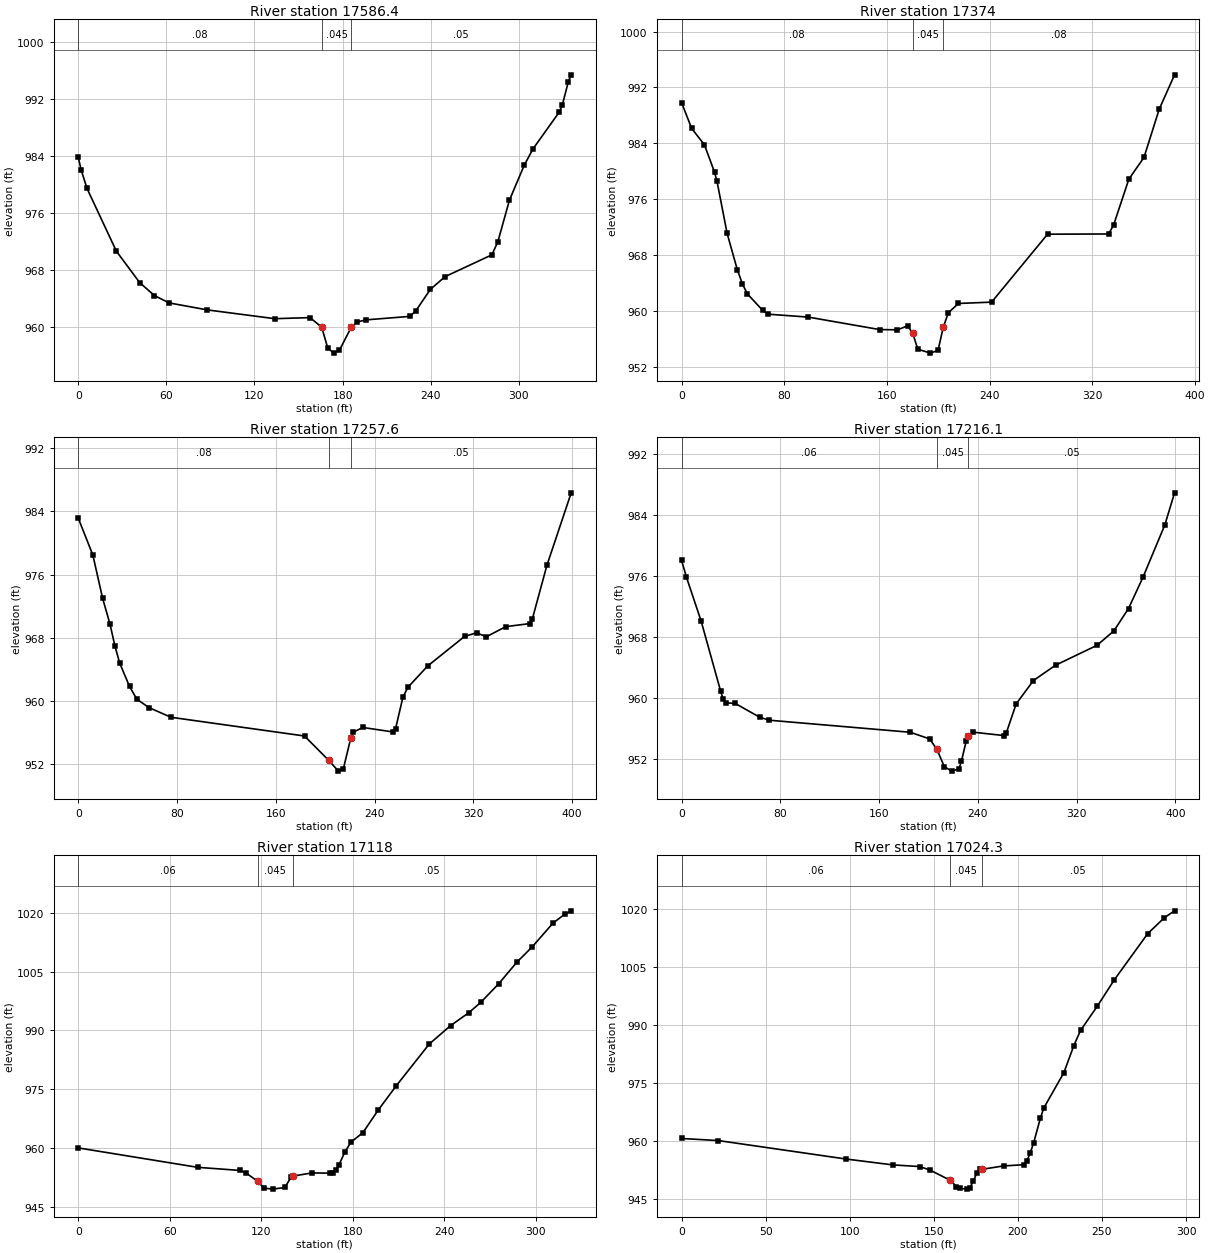
Type RM Length L Ch R = 1 ,17586.4 ,210,212.4,212.6
XS GIS Cut Line= 2
     1652517.867      581515.165     1652229.673       581687.04
#Sta/Elev= 30
       0  983.87       2  982.08       6  979.47      26  970.67    41.9  966.26
    51.9  964.45    61.9  963.42    87.9  962.44   133.8  961.21   157.8  961.36
   165.8  960.01   169.8  957.14   173.8  956.38   177.8  956.77   185.8  959.98
   189.8  960.73   195.7  961.04   225.7  961.53   229.7  962.27   239.7  965.31
   249.7   967.1   281.6  970.16   285.6  971.95   293.6  977.85   303.6  982.71
   309.6  985.02   327.6  990.21   329.6   991.2   333.6   994.4   335.6   995.4
#Mann= 3 , 0 , 0
       0     .08       0   165.8    .045       0   185.8     .05       0
Bank Sta=165.8,185.8
XS Rating Curve= 0 ,0
Exp/Cntr=0.3,0.1

Type RM Length L Ch R = 1 ,17374   ,115.7,116.4,109.5
XS GIS Cut Line= 4
     1652472.728      581341.554     1652375.506       581374.54
     1652227.937      581447.457     1652120.298      581492.596
#Sta/Elev= 30
       0  989.84     7.9  986.14    17.8  983.82    25.7  979.88    27.6   978.6
    35.5  971.14    43.4  965.97    47.4  963.92    51.3  962.49    63.2  960.14
    67.1   959.6    98.7  959.18   154.2   957.4   168.1  957.36     176  957.92
     180  956.91     184  954.59   193.9  954.03   199.8  954.44   203.8   957.7
   207.8   959.8   215.7  961.13   241.5  961.32   285.1  971.03   332.6  971.06
   336.5  972.33   348.4   978.9   360.2  982.01   372.1  988.93     384  993.81
#Mann= 3 , 0 , 0
       0     .08       0     180    .045       0   203.8     .08       0
Bank Sta=180,203.8
XS Rating Curve= 0 ,0
Exp/Cntr=0.3,0.1

Type RM Length L Ch R = 1 ,17257.6 ,42.6,41.5,33
XS GIS Cut Line= 6
     1652448.423      581284.262     1652318.215      581294.679
     1652259.187      581306.832     1652227.937      581324.193
     1652182.798       581397.11     1652108.145      581440.512
#Sta/Elev= 30
       0  983.16    11.9  978.46    19.8  972.97    25.7  969.76    29.7  966.98
    33.6  964.79    41.6  961.82    47.5  960.21    57.4  959.14    75.2  957.92
   183.3  955.55   202.8  952.48   210.8   951.1   214.8  951.41   220.8   955.3
   222.7  956.02   230.5  956.63   255.1  956.06     257  956.44     263  960.46
     267  961.71     283  964.41   312.9  968.16   322.7  968.62   330.6  968.12
   346.3   969.4   365.9  969.79   367.9  970.41   379.6  977.15   399.3  986.35
#Mann= 3 , 0 , 0
       0     .08       0   202.8    .045       0   220.8     .05       0
Bank Sta=202.8,220.8
XS Rating Curve= 0 ,0
Exp/Cntr=0.3,0.1

Type RM Length L Ch R = 1 ,17216.1 ,103.3,98.1,107.9
XS GIS Cut Line= 6
     1652425.853      581254.748     1652295.645      581265.165
     1652236.617      581277.318     1652205.367      581294.679
     1652160.228      581367.596     1652085.576      581410.998
#Sta/Elev= 30
       0   978.1       4  975.88    15.8  970.17    31.7  960.92    33.6  959.94
    35.6  959.42    43.5  959.33    63.3  957.52    71.2  957.13   185.2  955.55
   200.9  954.68   206.8  953.31   212.8  951.05   218.7  950.45   224.7  950.75
   226.7  951.76   230.5  954.36   232.4  955.12   236.2  955.56     261  955.12
     263  955.45     271  959.27     285  962.34   302.9  964.35   336.5  966.96
   350.2  968.86     362  971.79   373.8  975.92   391.4  982.75   399.3  986.97
#Mann= 3 , 0 , 0
       0     .06       0   206.8    .045       0   232.4     .05       0
Bank Sta=206.8,232.4
XS Rating Curve= 0 ,0
Exp/Cntr=0.3,0.1

Type RM Length L Ch R = 1 ,17118   ,84.5,93.6,102.7
XS GIS Cut Line= 4
     1652227.937       581147.11      1652177.59      581190.512
      1652092.52      581266.901     1651950.159      581268.637
#Sta/Elev= 30
       0  960.12    78.3  955.18   105.9  954.39   109.8   953.8   117.7  951.61
   121.7   949.9   127.6  949.63   135.5  950.05   139.4  952.59   140.8  952.95
   153.2  953.75     165   953.7     167  953.82     169  954.49     171  955.82
   174.9  959.14   178.8  961.56   186.7  964.02   196.6   969.7   208.5  975.92
   230.2  986.57   244.1  991.23     256  994.49   263.9  997.14   275.7 1001.89
   287.6 1007.38   297.5 1011.21   311.3 1017.32   319.2 1019.65   323.2 1020.44
#Mann= 3 , 0 , 0
       0     .06       0   117.7    .045       0   140.8     .05       0
Bank Sta=117.7,140.8
XS Rating Curve= 0 ,0
Exp/Cntr=0.3,0.1

Type RM Length L Ch R = 1 ,17024.3 ,45.2,45.2,45.2
XS GIS Cut Line= 2
     1652229.673      581112.387     1651951.895      581206.137
#Sta/Elev= 30
       0  960.69    21.9  960.15    97.7  955.39   125.6  953.87   141.6  953.44
   147.6  952.56   159.6  949.94   163.5  948.28   165.5  947.84   169.5  947.61
   171.5  948.03   173.5  949.64   175.5  951.73   177.5  952.71   178.7  952.73
   191.5   953.6   203.4  953.91   205.4  954.91   207.4  956.97   209.4  959.58
   213.4  965.91   215.4  968.54   227.4  977.71   233.3  984.69   237.3   988.6
   247.3  994.88   257.3 1001.62   277.2 1013.57   287.2 1017.73   293.2 1019.48
#Mann= 3 , 0 , 0
       0     .06       0   159.6    .045       0   178.7     .05       0
Bank Sta=159.6,178.7
XS Rating Curve= 0 ,0
Exp/Cntr=0.3,0.1

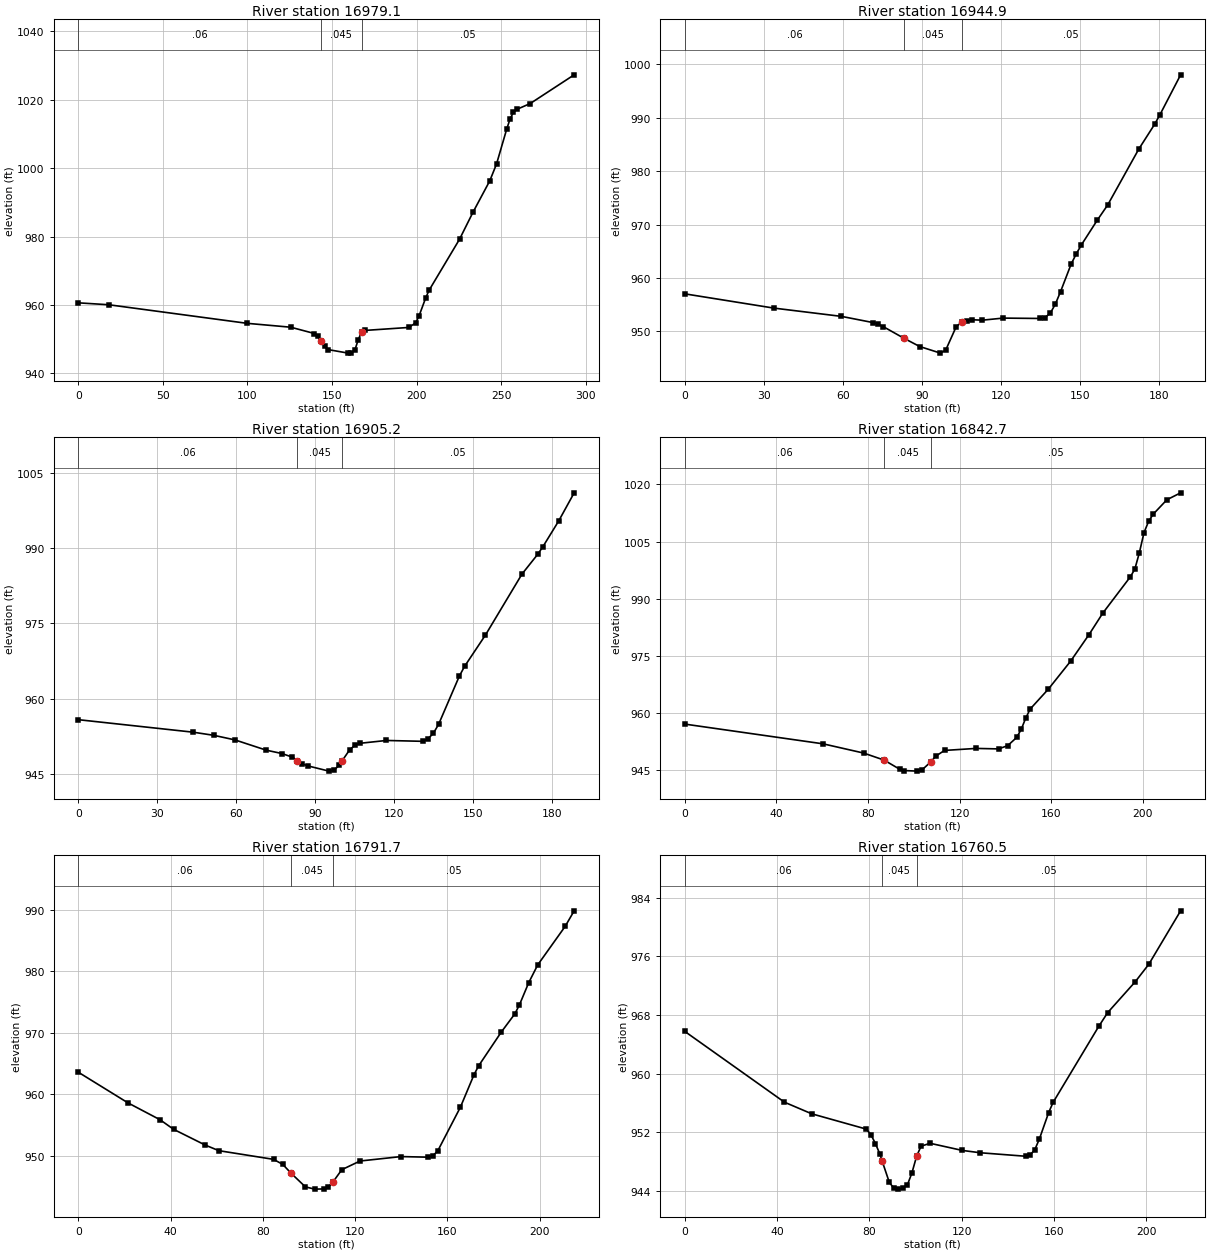
Type RM Length L Ch R = 1 ,16979.1 ,31.8,34.2,36.8
XS GIS Cut Line= 2
     1652207.103      581072.457     1651929.326      581166.207
#Sta/Elev= 30
       0  960.64      18  960.08    99.7  954.66   125.6  953.52   139.6  951.68
   141.6     951   143.6  949.52   145.6  947.89   147.6  946.99   159.6  945.95
   161.5  946.06   163.5  946.82   165.5  949.83   167.5  952.15   169.5  952.58
   195.4  953.45   199.4  954.76   201.4  956.72   205.4  962.07   207.4   964.3
   225.4   979.2   233.3  987.03   243.3  996.28   247.3  1001.2   253.3 1011.37
   255.3 1014.35   257.3  1016.3   259.3 1017.15   267.2 1018.85   293.2 1027.24
#Mann= 3 , 0 , 0
       0     .06       0   143.6    .045       0   167.5     .05       0
Bank Sta=143.6,167.5
XS Rating Curve= 0 ,0
Exp/Cntr=0.3,0.1

Type RM Length L Ch R = 1 ,16944.9 ,39.8,39.7,39.8
XS GIS Cut Line= 2
      1652146.34      581068.985     1651962.312      581108.915
#Sta/Elev= 30
       0  957.02    33.7  954.36    59.5   952.8    71.4  951.65    73.3  951.37
    75.3   950.9    83.2  948.71    89.2  947.16    97.1  945.92    99.1   946.5
   103.1   950.9   105.1  951.69     107  952.01     109  952.17     113  952.09
   120.9  952.48   134.8  952.41   136.8  952.58   138.8   953.4   140.7  955.07
   142.7  957.43   146.7  962.57   148.7  964.54   150.6  966.18   156.6  970.78
   160.6  973.66   172.4  984.12   178.4  988.75   180.4  990.52   188.3  998.03
#Mann= 3 , 0 , 0
       0     .06       0    83.2    .045       0   105.1     .05       0
Bank Sta=83.2,105.1
XS Rating Curve= 0 ,0
Exp/Cntr=0.3,0.1

Type RM Length L Ch R = 1 ,16905.2 ,61.5,62.5,62.7
XS GIS Cut Line= 2
     1652137.659       581030.79     1651953.631      581070.721
#Sta/Elev= 30
       0  955.82    43.6  953.33    51.5   952.7    59.5  951.79    71.4  949.74
    77.3  949.08    81.3  948.35    83.2  947.67    85.1     947    87.2  946.61
    95.2  945.57    97.1  945.76    99.1  946.76   100.1  947.57   103.1  949.86
   105.1  950.73     107  951.12     117  951.68   130.8  951.51   132.8  952.02
   134.8  953.09   136.8  954.87   144.7  964.51   146.7  966.46   154.6  972.68
   168.5  984.85   174.4  988.74   176.4  990.27   182.4   995.4   188.3 1001.03
#Mann= 3 , 0 , 0
       0     .06       0    83.2    .045       0   100.1     .05       0
Bank Sta=83.2,100.1
XS Rating Curve= 0 ,0
Exp/Cntr=0.3,0.1

Type RM Length L Ch R = 1 ,16842.7 ,52.1,51,49.3
XS GIS Cut Line= 4
     1652139.395       580968.29     1652078.631      580982.179
     1651976.201      581001.276     1651929.326      581018.637
#Sta/Elev= 30
       0  957.12    60.4  951.94    78.1  949.52      87  947.68    93.8  945.29
    95.8  944.93   101.6  944.78   103.6  945.12   107.6   947.3   109.5  948.68
   113.4  950.21   127.2  950.74     137  950.61     141  951.47   144.9  953.61
   146.9  955.74   148.8   958.6   150.8  961.07   158.7  966.27   168.5  973.66
   176.5  980.61   182.5  986.23   194.5  995.73   196.5  997.78   198.5 1002.13
   200.5 1007.35   202.5  1010.3   204.5 1012.19   210.5 1015.99   216.5 1017.81
#Mann= 3 , 0 , 0
       0     .06       0      87    .045       0   107.6     .05       0
Bank Sta=87,107.6
XS Rating Curve= 0 ,0
Exp/Cntr=0.3,0.1

Type RM Length L Ch R = 1 ,16791.7 ,31.2,31.2,31.4
XS GIS Cut Line= 3
     1652134.187      580888.429     1652085.576       580928.36
     1651938.006      580964.818
#Sta/Elev= 30
       0  963.62    21.6  958.62    35.4   955.9    41.3  954.34      55  951.78
    60.9  950.87    84.6  949.46    88.6  948.64    92.3  947.17    98.4  944.99
   102.4  944.62   106.3  944.65   108.3  944.94   110.3  945.75   114.2  947.78
   122.1  949.19   139.9  949.91   151.7  949.81   153.7  950.08   155.7  950.78
   165.6  957.94   171.5  963.22   173.5  964.66   183.3  970.14   189.2  973.11
   191.2  974.58   195.2  978.17   199.1  981.06     211  987.32   214.9  989.85
#Mann= 3 , 0 , 0
       0     .06       0    92.3    .045       0   110.3     .05       0
Bank Sta=92.3,110.3
XS Rating Curve= 0 ,0
Exp/Cntr=0.3,0.1

Type RM Length L Ch R = 1 ,16760.5 ,89.2,89.3,89.1
XS GIS Cut Line= 3
     1652127.242      580858.915     1652078.631      580898.846
     1651931.062      580935.304
#Sta/Elev= 30
       0  965.77    43.2  956.12      55  954.54    78.7  952.45    80.7  951.68
    82.6  950.49    84.6  949.02    85.5  948.13    88.6  945.23    90.6  944.37
    92.5  944.27    94.5  944.36    96.5  944.87    98.4  946.44   100.5  948.78
   102.4  950.12   106.3  950.52   120.2  949.55     128  949.23   147.8  948.75
   149.8  948.97   151.7  949.65   153.7  951.12   157.7   954.7   159.6  956.08
   179.4  966.45   183.3  968.34   195.2  972.53   201.1  974.92   214.9  982.21
#Mann= 3 , 0 , 0
       0     .06       0    85.5    .045       0   100.5     .05       0
Bank Sta=85.5,100.5
XS Rating Curve= 0 ,0
Exp/Cntr=0.3,0.1

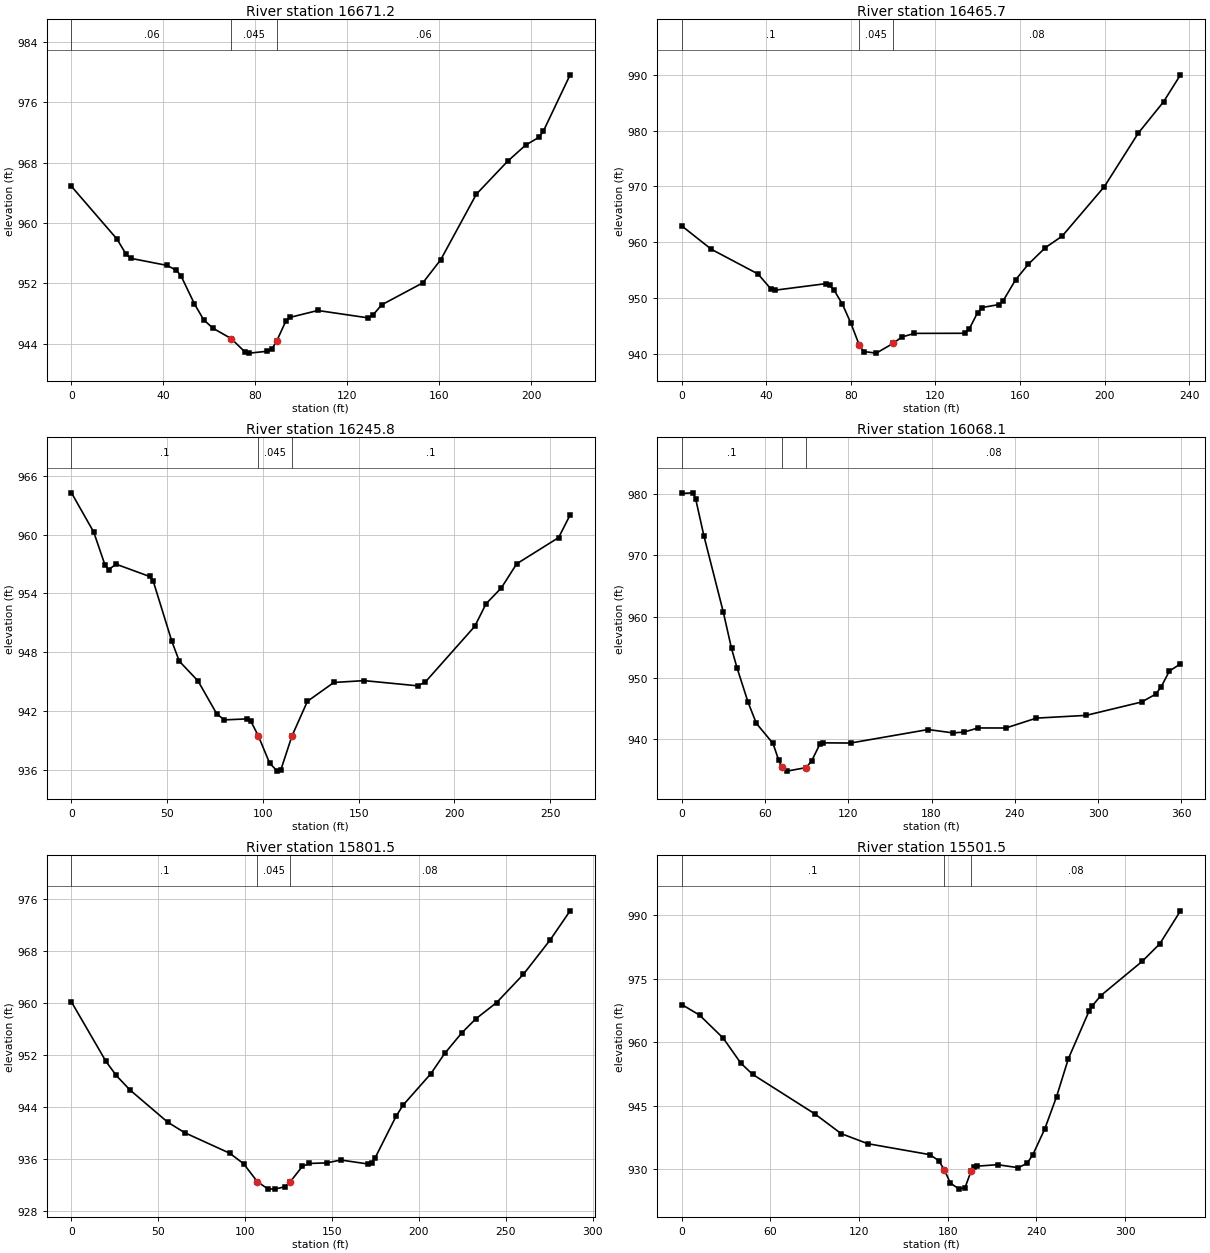
Type RM Length L Ch R = 1 ,16671.2 ,216.8,205.5,194.2
XS GIS Cut Line= 4
     1652095.992      580799.887      1652052.59      580813.776
     1651948.423      580839.818     1651899.812      580881.485
#Sta/Elev= 30
       0  964.84    19.8  957.86    23.8  955.84    25.8  955.31    41.6  954.37
    45.6  953.73    47.6  953.03    53.5  949.28    57.5  947.18    61.5  946.06
    69.5  944.68    75.4  942.93    77.4  942.75    85.3     943    87.3  943.34
    89.3  944.35    93.3     947    95.3   947.5   107.2   948.4   129.1  947.42
   131.1  947.76     135  949.15   152.9  952.06   160.7  955.13   176.2  963.81
   189.8  968.17   197.6   970.3   203.4  971.34   205.3  972.12     217  979.62
#Mann= 3 , 0 , 0
       0     .06       0    69.5    .045       0    89.3     .06       0
Bank Sta=69.5,89.3
XS Rating Curve= 0 ,0
Exp/Cntr=0.3,0.1

Type RM Length L Ch R = 1 ,16465.7 ,206.5,219.9,232.1
XS GIS Cut Line= 2
     1651970.992      580596.762     1651797.381      580756.485
#Sta/Elev= 30
       0  962.89      14   958.7      36  954.29      42  951.66      44  951.37
      68  952.54      70  952.22      72   951.4      76  948.84      80  945.43
      84  941.47      86  940.38      92  940.09     100  941.85     104  942.96
     110  943.63     134  943.65     136  944.45   139.9  947.33   141.9  948.26
   149.9  948.79   151.9  949.41   157.9  953.24   163.9  956.02   171.9  958.98
   179.9  961.06   199.9  969.95   215.9  979.52   227.9  985.16   235.9  989.99
#Mann= 3 , 0 , 0
       0      .1       0      84    .045       0     100     .08       0
Bank Sta=84,100
XS Rating Curve= 0 ,0
Exp/Cntr=0.3,0.1

Type RM Length L Ch R = 1 ,16245.8 ,184.2,177.6,169
XS GIS Cut Line= 4
     1651859.245      580463.198     1651805.425      580490.107
     1651714.279        580506.6     1651634.418      580578.649
#Sta/Elev= 30
       0  964.25    11.6  960.26    17.5   956.9    19.4  956.43    23.3  956.98
    40.8  955.73    42.7  955.25    52.4  949.13    56.3   947.1    66.1  945.08
    75.9  941.72    79.9  941.12    91.7  941.22    93.7  940.97    97.6  939.48
   103.5   936.7   107.5   935.9   109.4  936.06   115.1  939.46   123.2  943.01
     137  944.93   152.8  945.12   180.7  944.59   184.7  944.96   210.6  950.65
   216.5  952.95   224.5  954.57   232.5  957.02   254.4  959.69   260.4     962
#Mann= 3 , 0 , 0
       0      .1       0    97.6    .045       0   115.1      .1       0
Bank Sta=97.6,115.1
XS Rating Curve= 0 ,0
Exp/Cntr=0.3,0.1

Type RM Length L Ch R = 1 ,16068.1 ,261.3,266.6,268.1
XS GIS Cut Line= 4
     1651804.557      580300.003     1651749.002      580315.628
     1651672.613      580359.031     1651505.078      580491.843
#Sta/Elev= 30
       0   980.1       8   980.2      10  979.18    15.9  973.19    29.8  960.84
    35.8  954.84    39.8  951.65    47.8  946.02    53.7  942.62    65.7  939.35
    69.7  936.69    72.3  935.44    75.7  934.83    89.7  935.41    93.6  936.52
    99.6  939.28   101.6  939.44   121.6  939.41   177.5  941.61   195.5  941.06
   203.5   941.2   213.5  941.87   233.5  941.86   255.5  943.47   291.4  943.92
   331.4   946.1   341.4  947.36   345.4  948.53   351.4  951.15   359.4  952.31
#Mann= 3 , 0 , 0
       0      .1       0    72.3    .045       0    89.7     .08       0
Bank Sta=72.3,89.7
XS Rating Curve= 0 ,0
Exp/Cntr=0.3,0.1

Type RM Length L Ch R = 1 ,15801.5 ,281.7,300,320.1
XS GIS Cut Line= 4
     1651636.154      580119.448      1651562.37      580157.642
     1651421.745      580237.503      1651383.55      580255.732
#Sta/Elev= 30
       0  960.13    19.8  951.04    25.7  948.88    33.6  946.65    55.4  941.69
    65.3  940.06    91.1  936.93    99.1  935.32     107  932.57     113  931.46
     117  931.42     123  931.79   125.9  932.53     133  934.93     137  935.36
     147  935.44     155  935.89   170.9  935.27   172.9  935.41   174.9  936.25
   186.9   942.6   190.9   944.3   206.9  949.12   214.9  952.24   224.8  955.41
   232.8  957.54   244.8  960.04   260.2  964.37   275.6  969.64   287.1  974.11
#Mann= 3 , 0 , 0
       0      .1       0     107    .045       0   125.9     .08       0
Bank Sta=107,125.9
XS Rating Curve= 0 ,0
Exp/Cntr=0.3,0.1

Type RM Length L Ch R = 1 ,15501.5 ,254.8,255.5,256
XS GIS Cut Line= 2
     1651621.397      579984.031      1651316.23      579839.863
#Sta/Elev= 30
       0  968.86      12  966.37      28  960.95    39.9  955.06    47.9  952.41
    89.9  943.12   107.8  938.45   125.8  936.07   167.8  933.49   173.8   932.1
   177.7  929.91   181.7   926.8   187.7  925.36   191.7  925.74   195.7  929.53
   197.7  930.54   199.7  930.77   213.7  931.12   227.7  930.41   233.7  931.45
   237.6  933.49   245.6  939.51   253.6  947.12   261.6  956.09   275.6   967.3
   277.6  968.46   283.6  970.98   311.6  979.05   323.5  983.18   337.5  990.95
#Mann= 3 , 0 , 0
       0      .1       0   177.7    .045       0   195.7     .08       0
Bank Sta=177.7,195.7
XS Rating Curve= 0 ,0
Exp/Cntr=0.3,0.1

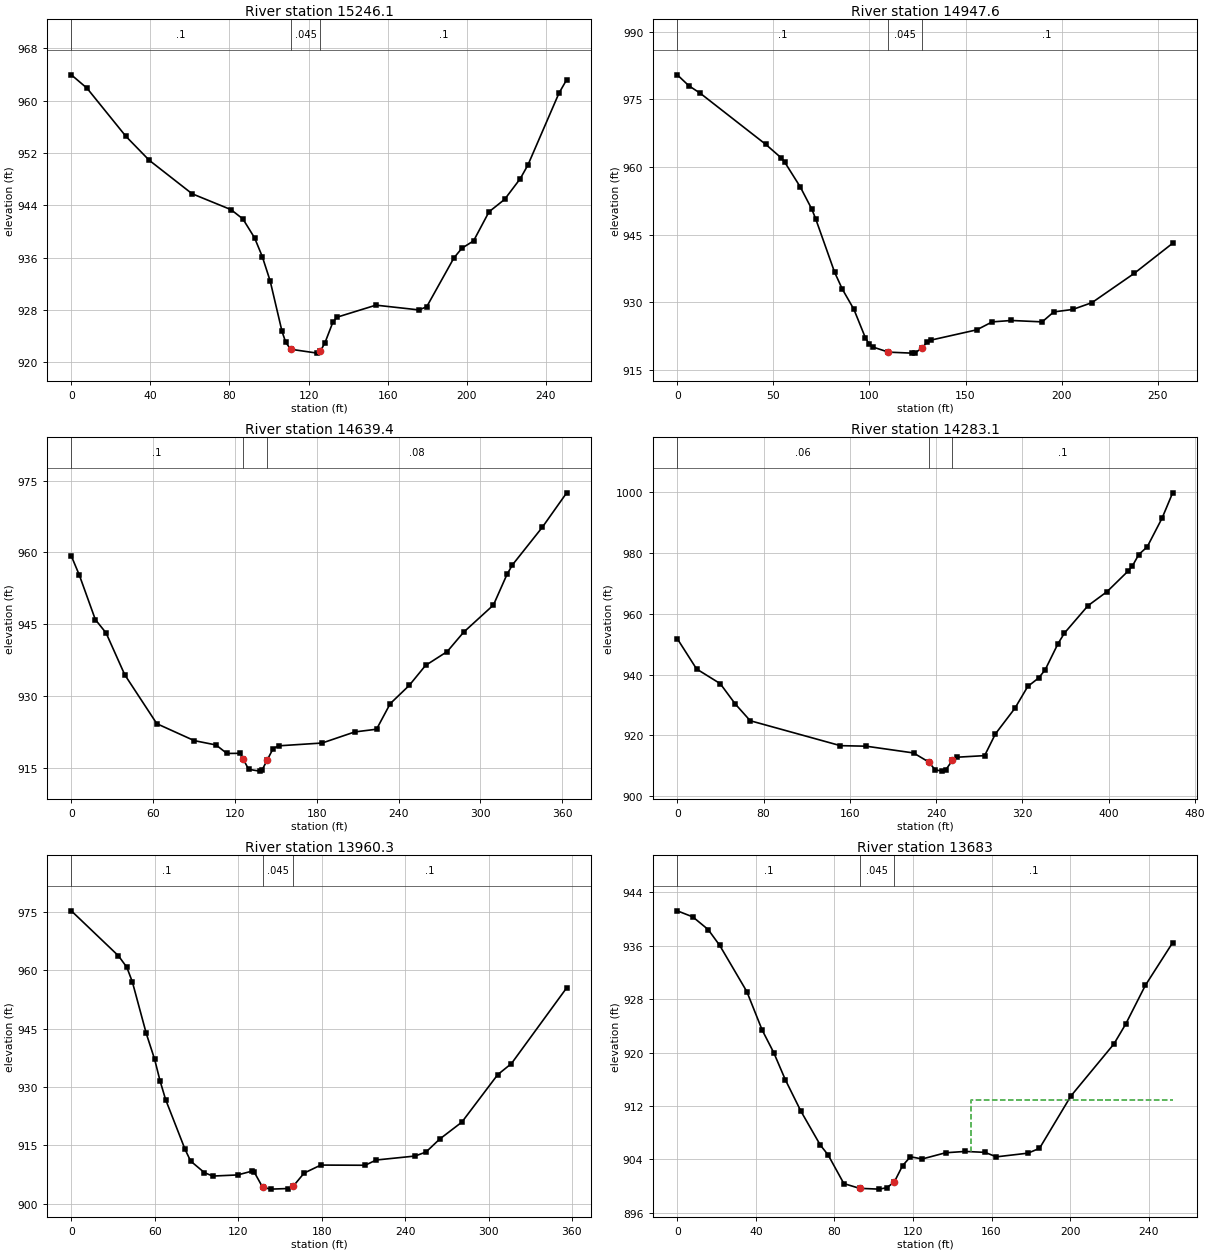
Type RM Length L Ch R = 1 ,15246.1 ,318.5,298.4,277.4
XS GIS Cut Line= 4
     1651637.022      579721.878     1651560.633      579676.739
     1651473.828      579633.336     1651411.328      579650.698
#Sta/Elev= 30
       0  963.93     7.9   961.9    27.6  954.54    39.4  950.88    61.1  945.76
    80.8  943.33    86.8  941.91    92.7  939.03    96.6  936.17   100.6  932.43
   106.6  924.72   108.5  923.04     111     922   124.4  921.41     126  921.72
   128.3  922.98   132.3  926.12   134.3  926.89   154.1  928.74   175.9  928.01
   179.8   928.5   193.6  935.98   197.6  937.44   203.5  938.56   211.3     943
   219.2   944.9   227.1  948.06     231  950.16   246.7  961.13   250.6  963.19
#Mann= 3 , 0 , 0
       0      .1       0     111    .045       0     126      .1       0
Bank Sta=111,126
XS Rating Curve= 0 ,0
Exp/Cntr=0.3,0.1

Type RM Length L Ch R = 1 ,14947.6 ,306.1,308.3,310.5
XS GIS Cut Line= 2
     1651616.189      579322.573      1651383.55      579433.684
#Sta/Elev= 30
       0  980.47       6  978.05      12  976.36      46  965.04      54  962.06
      56  961.01      64  955.58      70  950.65      72  948.52    81.9   936.6
    85.9  932.87    91.9   928.4    97.9  922.07    99.9  920.66   101.9  920.01
   109.9  918.89   121.9  918.67   123.9  918.77   127.2  919.75   129.9  921.04
   131.9  921.55   155.9  923.85   163.9  925.61   173.9  925.92   189.9  925.61
   195.9  927.82   205.8  928.37   215.8  929.88   237.8  936.38   257.8  943.07
#Mann= 3 , 0 , 0
       0      .1       0   109.9    .045       0   127.2      .1       0
Bank Sta=109.9,127.2
XS Rating Curve= 0 ,0
Exp/Cntr=0.3,0.1

Type RM Length L Ch R = 1 ,14639.4 ,341,356.2,370.3
XS GIS Cut Line= 4
      1651531.12      579095.142     1651444.314      579070.836
      1651281.12      579129.864     1651182.161      579140.281
#Sta/Elev= 30
       0  959.27     5.9  955.26    17.6     946    25.5  943.19    39.2  934.46
    62.7  924.25    90.1  920.72   106.1  919.81   114.1  918.04     124  918.07
     126  916.88     130  914.73     138  914.35     140  914.64   143.6  916.67
     148  919.06     152  919.63   183.9  920.22   207.8  922.53   223.8   923.1
   233.8  928.43   247.7  932.23   259.7  936.41   275.6  939.31   287.6  943.34
   309.5  949.03   319.4   955.4   323.4   957.4   345.3  965.25   363.2  972.45
#Mann= 3 , 0 , 0
       0      .1       0     126    .045       0   143.6     .08       0
Bank Sta=126,143.6
XS Rating Curve= 0 ,0
Exp/Cntr=0.3,0.1

Type RM Length L Ch R = 1 ,14283.1 ,341.5,322.9,303.9
XS GIS Cut Line= 4
     1651619.661      578865.975     1651466.883      578751.392
     1651296.745      578699.309     1651206.467      578701.045
#Sta/Elev= 30
       0  951.82    17.9  941.86    39.8  937.04    53.7  930.37    67.6  924.84
   151.2  916.64   175.1  916.46     219  914.24     233  911.28     239  908.72
     245  908.26     249  908.76     255  911.78     259  912.83   284.9  913.36
   294.9  920.51   312.9  928.91   324.9  936.12   334.9  938.89   340.9  941.51
   352.9  950.18   358.9  953.68   380.7  962.68   398.4  967.31     418  974.11
   421.9  975.77   427.8  979.51   435.6  982.03   449.4  991.49   459.2  999.81
#Mann= 3 , 0 , 0
       0     .06       0     233    .045       0     255      .1       0
Bank Sta=233,255
XS Rating Curve= 0 ,0
Exp/Cntr=0.3,0.1

Type RM Length L Ch R = 1 ,13960.3 ,276.7,277.3,277.7
XS GIS Cut Line= 4
      1651571.05      578332.989     1651510.286        578381.6
     1651371.397      578459.725     1651262.022        578506.6
#Sta/Elev= 30
       0  975.31    33.9  963.73    39.9   960.8    43.9  957.02    53.9  943.75
    59.9  937.12    63.8  931.57    67.8  926.76    81.8  913.93    85.8  910.93
    95.7  907.95   101.7  907.07   119.6  907.36   129.6  908.31   131.6  908.04
   137.6  904.17   143.4  903.71   155.5  903.86   159.5  904.43   167.4  907.84
   179.4   909.9   211.3  909.85   219.2   911.2   247.1  912.22     255  913.24
   264.9  916.59   280.8  920.94   306.6  933.16   316.5  936.02   356.2   955.5
#Mann= 3 , 0 , 0
       0      .1       0   137.6    .045       0   159.5      .1       0
Bank Sta=137.6,159.5
XS Rating Curve= 0 ,0
Exp/Cntr=0.3,0.1

Type RM Length L Ch R = 1 ,13683   ,250.7,263.2,275.4
XS GIS Cut Line= 3
     1651442.578      578126.392     1651380.078      578143.753
     1651216.883      578235.767
#Sta/Elev= 30
       0  941.25     7.9  940.34    15.7  938.45    21.6  936.07    35.4  929.15
    43.2  923.39    49.1     920      55  915.94    62.9  911.24    72.8  906.15
    76.8  904.66    84.8  900.37    92.8  899.66   102.7  899.54   106.7  899.75
   110.5  900.62   114.7  903.06   118.7  904.39   124.7  904.06   136.6  904.99
   146.6  905.19   156.6  905.05   162.5  904.38   178.5  904.93   184.4  905.65
   200.4   913.5   222.3   921.3   228.3  924.28   238.3  930.08   252.2  936.48
#Mann= 3 , 0 , 0
       0      .1       0    92.8    .045       0   110.5      .1       0
#XS Ineff= 2 , 0
                           149.6          912.96
Permanent Ineff=
       F       F
Bank Sta=92.8,110.5
XS Rating Curve= 0 ,0
Exp/Cntr=0.3,0.1

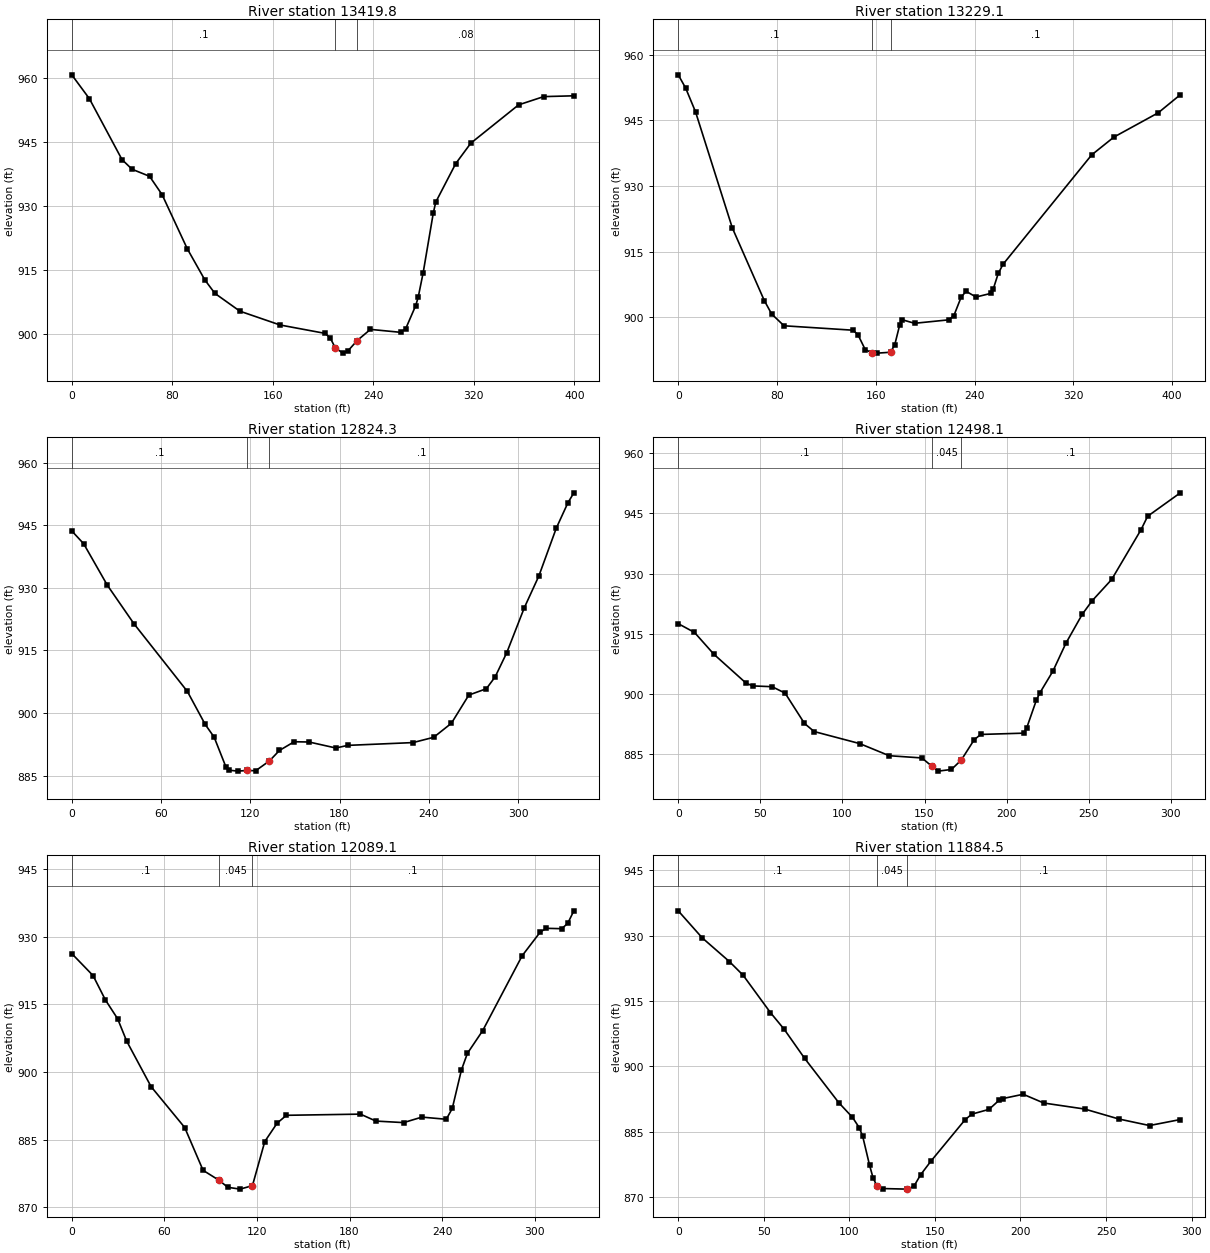
Type RM Length L Ch R = 1 ,13419.8 ,184.5,190.7,196.8
XS GIS Cut Line= 2
     1651496.397      577925.003     1651097.092      577911.114
#Sta/Elev= 30
       0  960.76      14  955.17      40  940.87      48  938.61    61.9  936.96
    71.9  932.65    91.9  919.98   105.9  912.66   113.9   909.5   133.8  905.32
   165.8  902.08   201.8   900.1   205.8  898.99   209.8  896.68   215.8  895.48
   219.8     896   227.1  898.42   237.7  901.05   261.7  900.36   265.7  901.16
   273.7   906.6   275.7  908.56   279.7  914.38   287.7  928.29   289.7  930.91
   305.6  939.94   317.6  944.73   355.6  953.71   375.6  955.65   399.6  955.84
#Mann= 3 , 0 , 0
       0      .1       0   209.8    .045       0   227.1     .08       0
Bank Sta=209.8,227.1
XS Rating Curve= 0 ,0
Exp/Cntr=0.3,0.1

Type RM Length L Ch R = 1 ,13229.1 ,406.7,404.7,401.9
XS GIS Cut Line= 4
     1651466.883      577780.906     1651400.911      577758.336
     1651220.356      577701.045     1651086.675      577638.545
#Sta/Elev= 30
       0   955.4       6  952.38      14  946.95    43.8  920.42    69.7  903.82
    75.7  900.73    85.7  898.05   141.5  897.04   145.5  896.05   151.5  892.59
     157   891.9   161.4   891.8     172     892   175.4  893.73   179.4  898.25
   181.4  899.43   191.4  898.62   219.3  899.41   223.3  900.39   229.2  904.61
   233.2  905.93   241.2  904.62   253.2  905.45   255.2  906.47   259.2     910
   263.1   912.1   334.9   937.1   352.9  941.17   388.8  946.72   406.7  950.85
#Mann= 3 , 0 , 0
       0      .1       0     157    .045       0     172      .1       0
Bank Sta=157,172
XS Rating Curve= 0 ,0
Exp/Cntr=0.3,0.1

Type RM Length L Ch R = 1 ,12824.3 ,318.7,326.2,333
XS GIS Cut Line= 4
     1651543.272      577390.281     1651459.939      577352.086
     1651305.425      577320.836     1651230.772      577273.961
#Sta/Elev= 30
       0   943.7       8  940.62    23.9  930.67    41.8  921.42    77.7  905.18
    89.7  897.25    95.7  894.21   103.6  887.07   105.6  886.28   111.6  886.05
   117.9  886.21   123.6  886.14   132.9  888.51   139.6  891.01   149.5   893.1
   159.5  893.04   177.5   891.6   185.5  892.23   229.4   892.9   243.3  894.17
   255.2  897.54   266.9   904.3   278.7  905.83   284.6  908.67   292.4  914.47
   304.2  925.26     314   932.9   325.7  944.37   333.5  950.44   337.5  952.84
#Mann= 3 , 0 , 0
       0      .1       0   117.9    .045       0   132.9      .1       0
Bank Sta=117.9,132.9
XS Rating Curve= 0 ,0
Exp/Cntr=0.3,0.1

Type RM Length L Ch R = 1 ,12498.1 ,408.4,409,408.8
XS GIS Cut Line= 4
     1651616.189      577135.073     1651546.745      577056.948
     1651454.731      577004.864     1651364.453      576973.614
#Sta/Elev= 30
       0  917.48     9.9  915.29    21.7  909.85    41.4   902.6    45.4  901.94
    57.2  901.74    65.1  900.13    76.9  892.56    82.8  890.54   110.5  887.54
   128.5  884.51   148.4  883.95   154.4  881.91   158.4  880.66   166.4  881.08
   172.4  883.43   180.3  888.53   184.3  889.82   210.3  890.14   212.2   891.4
   218.2  898.47   220.2  900.15   228.2  905.62   236.1  912.58   246.1  919.84
   252.1   923.2     264  928.52   281.9  940.96   285.9   944.3   305.8  950.15
#Mann= 3 , 0 , 0
       0      .1       0   154.4    .045       0   172.4      .1       0
Bank Sta=154.4,172.4
XS Rating Curve= 0 ,0
Exp/Cntr=0.3,0.1

Type RM Length L Ch R = 1 ,12089.1 ,216.2,204.6,192.7
XS GIS Cut Line= 4
     1651756.814      576751.392     1651699.522      576702.781
     1651577.995      576633.336      1651468.62      576619.448
#Sta/Elev= 30
       0  926.26    13.8  921.38    21.8  915.98    29.7  911.82    35.6  906.84
    51.4  896.76    73.2  887.69    85.1   878.2    95.5  875.98   101.1  874.44
   109.1  874.03   117.1   874.8   125.1  884.59   133.1  888.66   139.1   890.4
   187.1  890.66   197.1  889.12   215.1  888.78   226.9     890   242.7  889.52
   246.6  891.91   252.5   900.4   256.4  904.13   266.3  909.16   291.9  925.78
   303.7  931.06   307.6  931.86   317.5  931.78   321.4  932.94   325.4  935.74
#Mann= 3 , 0 , 0
       0      .1       0    95.5    .045       0   117.1      .1       0
Bank Sta=95.5,117.1
XS Rating Curve= 0 ,0
Exp/Cntr=0.3,0.1

Type RM Length L Ch R = 1 ,11884.5 ,315.7,316.3,315.9
XS GIS Cut Line= 2
     1651867.925      576503.128     1651574.522      576503.128
#Sta/Elev= 30
       0  935.68      14  929.48    29.9  924.03    37.9   920.9    53.9   912.3
    61.9  908.49    73.8  901.84    93.8  891.64   101.8  888.27   105.8  885.89
   107.8  883.89   111.8  877.28   113.8  874.43   116.1  872.52   119.8  871.91
   133.7  871.78   137.7  872.43   141.7  875.11   147.7  878.22   167.7  887.75
   171.6     889   181.6  890.09   187.6  892.22   189.6  892.57   201.6  893.56
   213.6  891.55   237.5  890.17   257.5  887.88   275.4  886.38   293.4  887.76
#Mann= 3 , 0 , 0
       0      .1       0   116.1    .045       0   133.7      .1       0
Bank Sta=116.1,133.7
XS Rating Curve= 0 ,0
Exp/Cntr=0.3,0.1

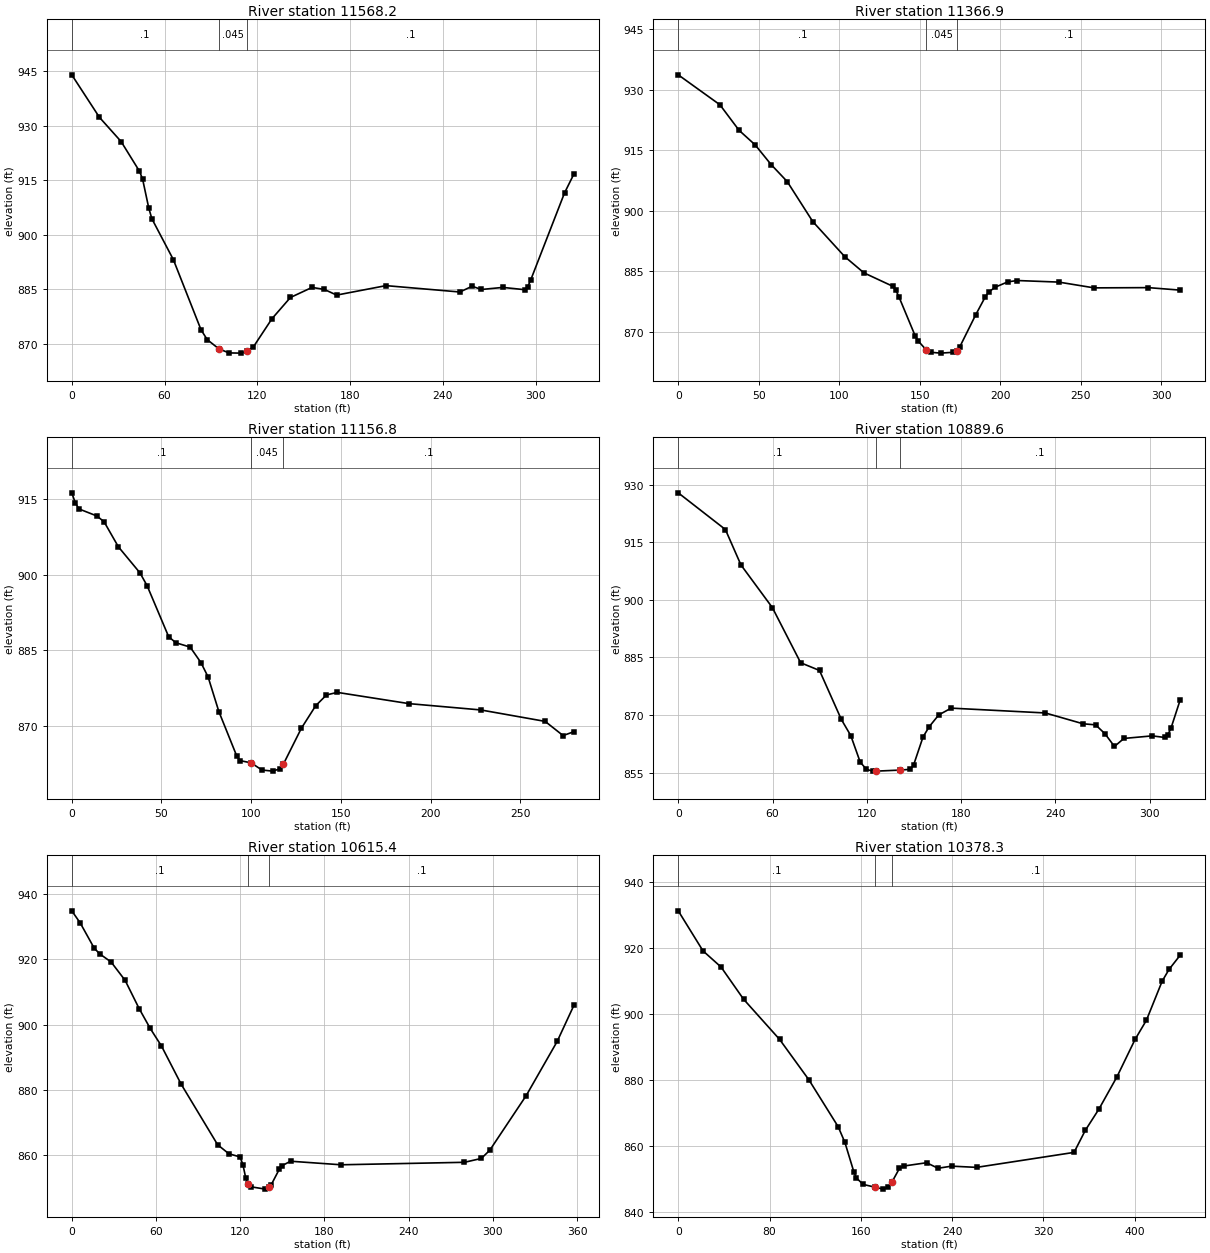
Type RM Length L Ch R = 1 ,11568.2 ,201.6,201.3,200.4
XS GIS Cut Line= 2
     1651871.397      576188.892     1651546.745      576187.156
#Sta/Elev= 30
       0  943.95    17.9  932.27    31.9  925.63    43.8  917.46    45.8  915.32
    49.8  907.34    51.8  904.42    65.7  893.19    83.6  873.91    87.6  871.22
      95  868.73   101.6  867.57   109.6  867.51   113.5  868.02   117.5  869.25
   129.5  876.98   141.4  882.79   155.4  885.56   163.3  885.01   171.3  883.45
   203.2  886.05     251   884.3   258.9  885.88   264.9  884.99   278.8  885.56
   292.8  884.94   294.8  885.67   296.8   887.6   318.7  911.54   324.7  916.67
#Mann= 3 , 0 , 0
       0      .1       0      95    .045       0   113.5      .1       0
Bank Sta=95,113.5
XS Rating Curve= 0 ,0
Exp/Cntr=0.3,0.1

Type RM Length L Ch R = 1 ,11366.9 ,218.8,210.1,201.3
XS GIS Cut Line= 3
     1651867.925      576081.253     1651774.175      575989.239
      1651593.62      575992.711
#Sta/Elev= 30
       0   933.7    25.9  926.28    37.8  919.95    47.8  916.34    57.7  911.47
    67.7  907.26    83.6  897.34   103.5  888.64   115.4  884.63   133.4  881.29
   135.3  880.28   137.3  878.54   147.2  869.06   149.2  867.71   154.2   865.5
   157.2  864.94   163.1  864.74     171  864.95     173  865.34     175  866.33
   184.9  874.27   190.9  878.75   192.9  879.84   196.8  881.05   204.8   882.4
   210.7  882.73   236.5  882.34   258.4  880.91   292.1  880.97     312  880.35
#Mann= 3 , 0 , 0
       0      .1       0   154.2    .045       0     173      .1       0
Bank Sta=154.2,173
XS Rating Curve= 0 ,0
Exp/Cntr=0.3,0.1

Type RM Length L Ch R = 1 ,11156.8 ,258.3,267.2,275.8
XS GIS Cut Line= 2
     1651808.897      575742.711     1651551.953      575853.823
#Sta/Elev= 30
       0  916.21       2   914.2       4  913.02      14  911.62      18  910.48
      26   905.5      38  900.35      42   897.8      54   887.7      58  886.49
      66  885.63      72  882.56      76  879.71      82  872.85      92  864.01
      94  863.11     100  862.68     106  861.26     112  861.04     116  861.49
     118  862.44     128  869.54     136  874.01     142  876.14     148  876.65
     188  874.42     228  873.17   263.9   870.9   273.9  868.09   279.9  868.85
#Mann= 3 , 0 , 0
       0      .1       0     100    .045       0     118      .1       0
Bank Sta=100,118
XS Rating Curve= 0 ,0
Exp/Cntr=0.3,0.1

Type RM Length L Ch R = 1 ,10889.6 ,273.2,274.2,274.4
XS GIS Cut Line= 2
     1651807.161      575522.225     1651487.717       575529.17
#Sta/Elev= 30
       0   927.9      30  918.34    39.9  909.11    59.9  897.98    77.9  883.61
    89.9   881.6   103.8  868.82   109.8  864.62   115.8  857.71   119.8  855.81
   123.8  855.36   126.1  855.36   141.1  855.63   147.8  855.83   149.8  856.99
   155.8  864.29   159.8  866.99   165.8  870.02   173.7  871.78   233.6  870.52
   257.6   867.7   265.6  867.42   271.6  865.08   277.6  861.79   283.6  863.88
   301.6  864.55   309.5  864.14   311.5   864.8   313.5  866.48   319.5  874.02
#Mann= 3 , 0 , 0
       0      .1       0   126.1    .045       0   141.1      .1       0
Bank Sta=126.1,141.1
XS Rating Curve= 0 ,0
Exp/Cntr=0.3,0.1

Type RM Length L Ch R = 1 ,10615.4 ,253.2,237.1,220.3
XS GIS Cut Line= 2
     1651800.564      575252.086     1651442.925       575250.35
#Sta/Elev= 30
       0  934.85       6  931.15      16  923.41      20  921.64      28   919.2
      38  913.57      48  904.92    55.9  898.84    63.9  893.47    77.9   881.8
   103.9  863.26   111.9   860.5   119.9  859.53   121.9  857.16   123.9  853.12
   125.6   851.2   127.9  850.37   137.9  849.68   140.6  850.22   141.9  850.88
   147.8  855.76   149.8  856.86   155.8  858.22   191.8  857.13   279.7  857.89
   291.7  859.07   297.7  861.57   323.7  878.33   345.7  894.86   357.6  905.89
#Mann= 3 , 0 , 0
       0      .1       0   125.6    .045       0   140.6      .1       0
Bank Sta=125.6,140.6
XS Rating Curve= 0 ,0
Exp/Cntr=0.3,0.1

Type RM Length L Ch R = 1 ,10378.3 ,154.3,148.8,143.4
XS GIS Cut Line= 4
     1651786.328      575046.531     1651647.439      575001.392
     1651518.967      575114.239      1651406.12       575162.85
#Sta/Elev= 30
       0  931.35    21.7  919.18    37.5  914.28    57.2  904.52    88.8  892.29
   114.5     880   140.1  865.78     146  861.02     154  851.89     156  850.23
     162  848.23   172.3   847.4   179.8   846.8   183.8  847.36   187.3  848.98
   193.8  853.09   197.7  853.82   217.6  854.82   227.6  853.14   239.5  853.78
   261.4  853.41   346.8  857.96   356.7  864.68   368.6  871.12   384.4  880.93
   400.3   892.3   410.2  898.11     424  909.98     430  913.54   439.9  917.92
#Mann= 3 , 0 , 0
       0      .1       0   172.3    .045       0   187.3      .1       0
Bank Sta=172.3,187.3
XS Rating Curve= 0 ,0
Exp/Cntr=0.3,0.1