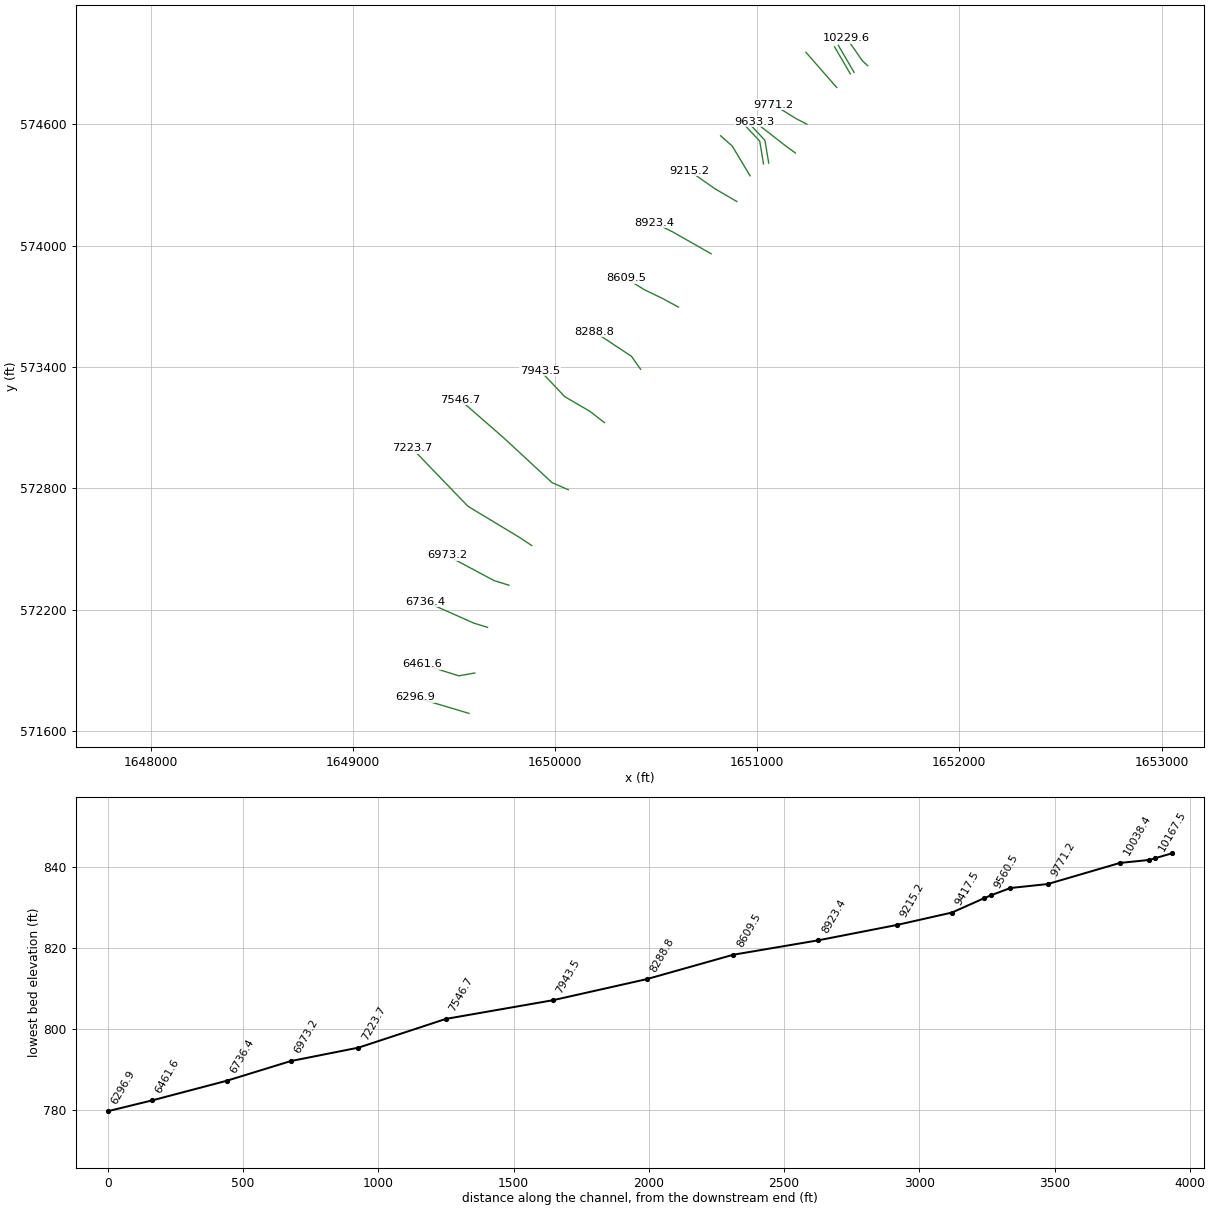
HEC-RAS study PETERSRUN.prj: PETERSRUN

--- PETERSRUN.g01 (geometry) --- (continued)

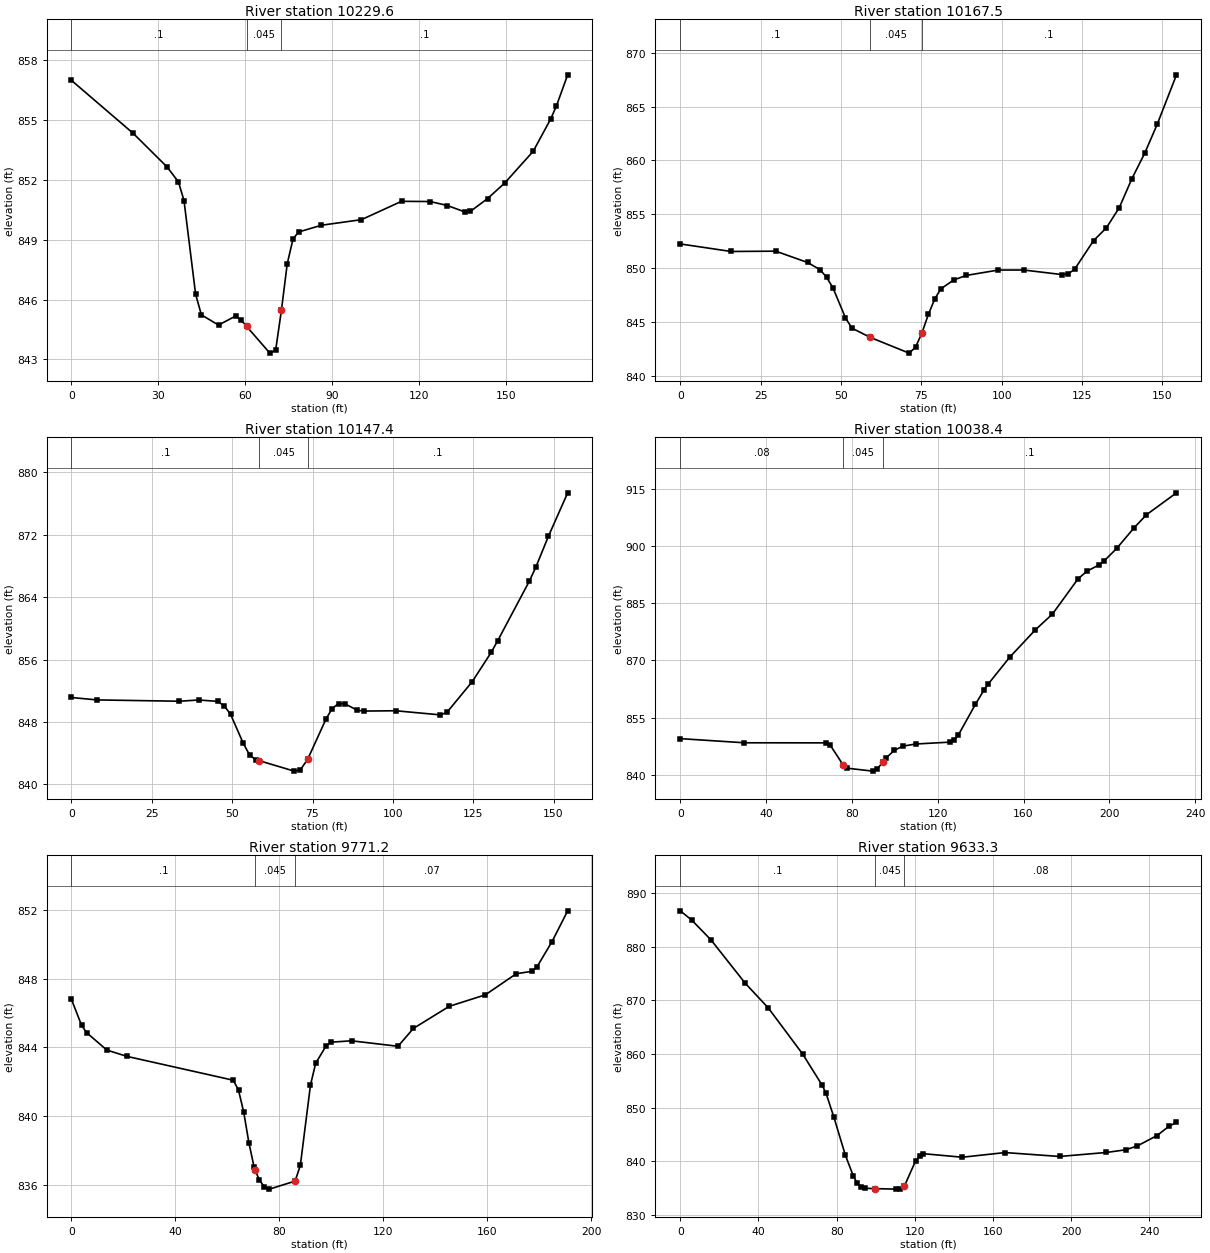
Type RM Length L Ch R = 1 ,10229.6 ,63.7,62,60.1
XS GIS Cut Line= 3
     1651546.727      574889.602     1651521.033      574913.213
     1651443.255      575025.019
#Sta/Elev= 30
       0     857    21.3  854.34      33  852.65    36.9   851.9    38.8  850.97
    42.8  846.27    44.8  845.23    50.7  844.72    56.6  845.17    58.6  844.96
    60.4  844.65    68.4  843.31    70.4  843.45    72.4  845.47    74.4   847.8
    76.4  849.04    78.3  849.39    86.2  849.73     100  850.01   113.8  850.93
   123.7  850.92   129.6  850.72   135.6   850.4   137.5  850.42   143.5  851.07
   149.4  851.85   159.2  853.44   165.2  855.05   167.2  855.71   171.1  857.28
#Mann= 3 , 0 , 0
       0      .1       0    60.4    .045       0    72.4      .1       0
Bank Sta=60.4,72.4
XS Rating Curve= 0 ,0
Exp/Cntr=0.3,0.1

Type RM Length L Ch R = 1 ,10167.5 ,20.1,20.2,20.1
XS GIS Cut Line= 2
     1651479.366      574856.963     1651401.588      574990.297
#Sta/Elev= 30
       0  852.25    15.8  851.55    29.7  851.58    39.6  850.53    43.5  849.86
    45.5  849.17    47.5  848.18    51.4  845.39    53.4  844.44    59.1  843.58
    71.2  842.12    73.2  842.67    75.2     844    77.2  845.72    79.2  847.16
    81.1  848.09    85.1  848.91      89  849.33      99  849.83   106.9  849.83
   118.7  849.41   120.7  849.48   122.7   849.9   128.6  852.56   132.6  853.75
   136.6  855.62   140.5  858.29   144.5  860.66   148.4  863.35   154.4  867.94
#Mann= 3 , 0 , 0
       0      .1       0    59.1    .045       0    75.2      .1       0
Bank Sta=59.1,75.2
XS Rating Curve= 0 ,0
Exp/Cntr=0.3,0.1

Type RM Length L Ch R = 1 ,10147.4 ,104.5,109,113.1
XS GIS Cut Line= 2
     1651460.616      574849.325     1651382.838      574982.658
#Sta/Elev= 30
       0  851.14     7.9  850.83    33.6  850.66    39.6  850.82    45.5  850.64
    47.5  850.08    49.5  848.99    53.4  845.31    55.4  843.79    57.4  843.12
    58.5  843.03    69.3   841.7    71.2  841.85    73.5  843.22    79.2  848.38
    81.1  849.72    83.1  850.36    85.1  850.32      89   849.5      91   849.4
   100.9  849.44   114.8  848.91   116.8  849.22   124.7  853.17   130.6  856.92
   132.6   858.4   142.5  866.08   144.5  867.86   148.4   871.8   154.4  877.38
#Mann= 3 , 0 , 0
       0      .1       0    58.5    .045       0    73.5      .1       0
Bank Sta=58.5,73.5
XS Rating Curve= 0 ,0
Exp/Cntr=0.3,0.1

Type RM Length L Ch R = 1 ,10038.4 ,260.3,267.2,273.9
XS GIS Cut Line= 2
     1651393.255      574781.963     1651241.189      574956.253
#Sta/Elev= 30
       0  849.48    29.9  848.39    67.8  848.37    69.8  847.83    75.8  842.69
    77.8  841.73    89.7  840.96    91.7  841.45    94.3  843.24    95.7   844.3
    99.7  846.38   103.7   847.5   109.7  848.07   125.6  848.56   127.6  849.08
   129.6  850.41   137.6  858.51   141.6  862.26   143.6  863.84   153.5  870.79
   165.5     878   173.5  882.16   185.4  891.37   189.4  893.32   195.4   895.1
   197.4  895.98   203.4  899.34   211.4  904.67   217.3  908.18   231.3  913.93
#Mann= 3 , 0 , 0
       0     .08       0    75.8    .045       0    94.3      .1       0
Bank Sta=75.8,94.3
XS Rating Curve= 0 ,0
Exp/Cntr=0.3,0.1

Type RM Length L Ch R = 1 ,9771.2  ,140.2,137.9,135.3
XS GIS Cut Line= 3
     1651246.033      574600.713     1651193.949      574627.102
     1651081.449      574697.241
#Sta/Elev= 30
       0   846.8     3.9  845.29     5.8  844.87    13.6  843.85    21.4  843.48
    62.3  842.09    64.3  841.51    66.3  840.23    68.3  838.44    70.3  837.02
    70.7  836.87    72.2   836.3    74.2  835.88    76.2  835.74    86.1  836.21
    88.1  837.13      92  841.81      94  843.08      98  844.09    99.9  844.31
   107.8  844.39   125.7  844.07   131.6  845.11   145.4   846.4   159.3  847.07
   171.2   848.3   177.1  848.44   179.1  848.68     185  850.18     191  851.97
#Mann= 3 , 0 , 0
       0      .1       0    70.7    .045       0    86.1     .07       0
Bank Sta=70.7,86.1
XS Rating Curve= 0 ,0
Exp/Cntr=0.3,0.1

Type RM Length L Ch R = 1 ,9633.3  ,89.4,72.7,55.6
XS GIS Cut Line= 3
     1651189.106      574457.989     1651137.022      574496.184
     1650987.717      574612.503
#Sta/Elev= 30
       0  886.75     5.9     885    15.7  881.32    33.3  873.19      45  868.62
    62.6     860    72.6  854.17    74.6  852.63    78.5  848.31    84.5  841.06
    88.5  837.25    90.5  835.85    92.5  835.17    94.5  834.92    99.7  834.85
   110.4  834.76   112.4  834.78   114.7  835.36   120.4  840.03   122.4  840.92
   124.4  841.38   144.3  840.72   166.2  841.59   194.1  840.86     218  841.61
     228  842.11   233.9  842.84   243.9  844.76   249.9  846.46   253.9  847.23
#Mann= 3 , 0 , 0
       0      .1       0    99.7    .045       0   114.7     .08       0
Bank Sta=99.7,114.7
XS Rating Curve= 0 ,0
Exp/Cntr=0.3,0.1

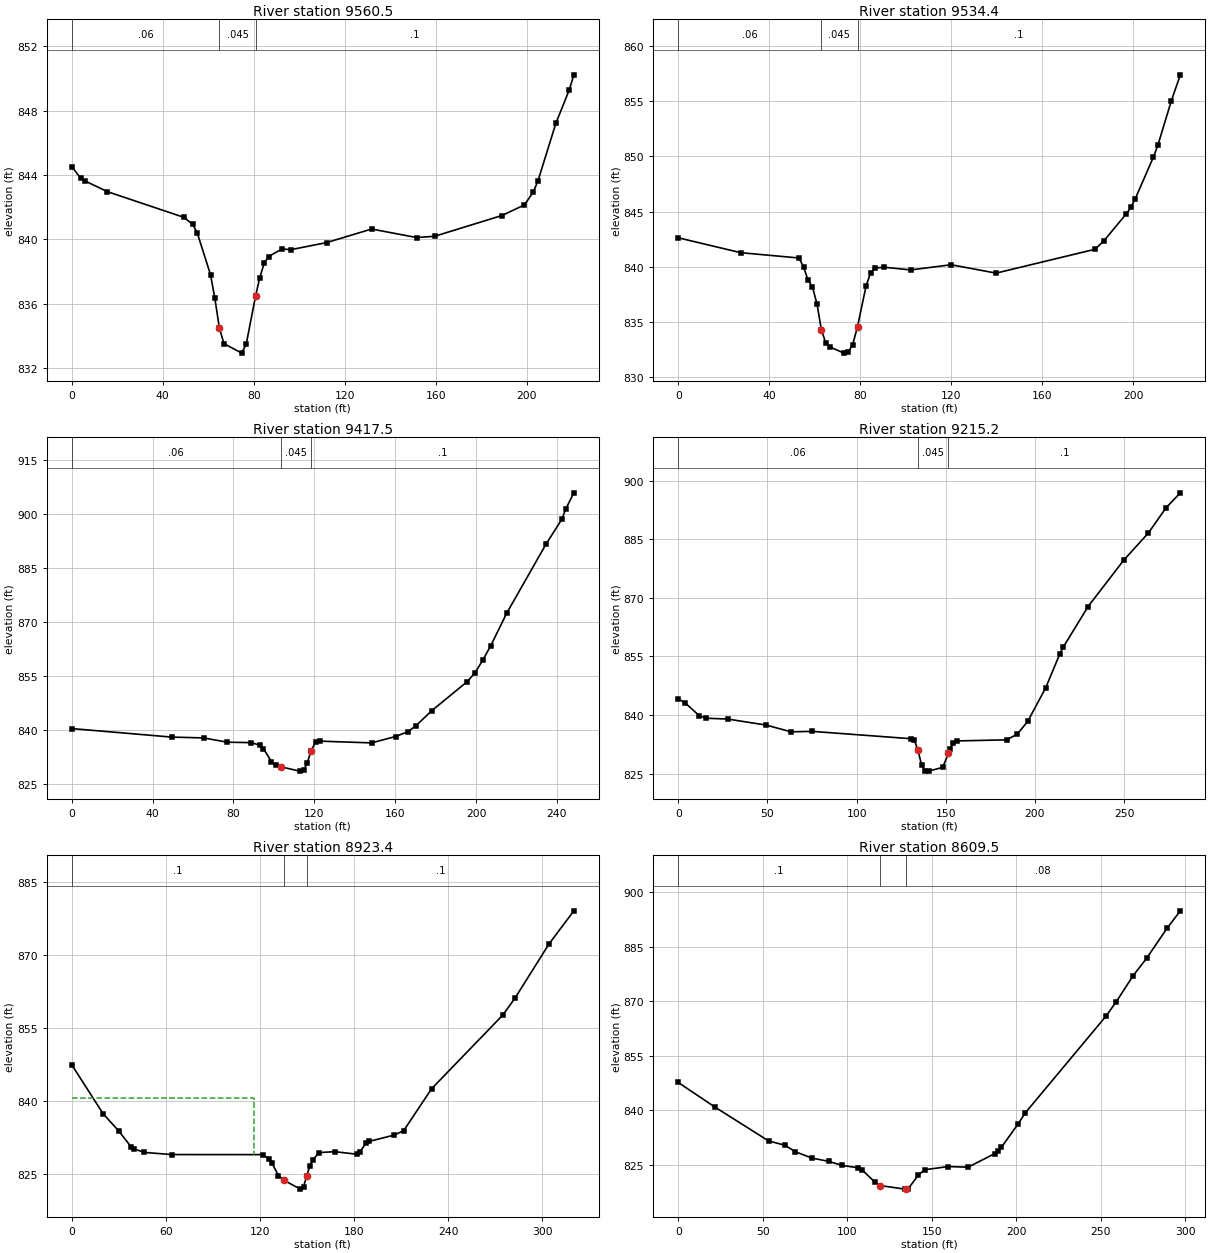
Type RM Length L Ch R = 1 ,9560.5  ,26.2,26.1,26.3
XS GIS Cut Line= 3
     1651057.144      574408.352     1651038.394      574520.852
     1650965.477       574598.63
#Sta/Elev= 30
       0  844.52     3.9   843.8     5.9  843.62    15.7  842.96    49.2  841.37
    53.1  840.94    55.1  840.42      61   837.8    62.9  836.33    64.9  834.48
    66.9  833.52    74.7  832.93    76.7   833.5    80.8  836.48    82.6   837.6
    84.6  838.53    86.5  838.93    92.4   839.4    96.4  839.36   112.1   839.8
   131.8  840.64   151.6  840.11   159.5  840.19   189.1  841.48     199  842.14
   202.9  842.95   204.9  843.62   212.8  847.21   218.7  849.29   220.7  850.22
#Mann= 3 , 0 , 0
       0     .06       0    64.9    .045       0    80.8      .1       0
Bank Sta=64.9,80.8
XS Rating Curve= 0 ,0
Exp/Cntr=0.3,0.1

Type RM Length L Ch R = 1 ,9534.4  ,108.3,117,125.2
XS GIS Cut Line= 3
     1651031.449      574404.186     1651012.699      574516.686
     1650939.783      574594.463
#Sta/Elev= 30
       0  842.63    27.5  841.28    53.1   840.8    55.1  839.98      57  838.83
      59  838.18      61  836.64    62.9  834.32    64.9  833.07    66.9  832.73
    72.8  832.19    74.7  832.28    76.7  832.97    78.8  834.58    82.6   838.3
    84.6  839.48    86.5  839.89    90.4  839.97   102.2  839.72     120  840.19
   139.7  839.43   183.2  841.59   187.1  842.35     197  844.81     199  845.38
   200.9  846.17   208.8   849.9   210.8  850.99   216.7  854.99   220.7  857.38
#Mann= 3 , 0 , 0
       0     .06       0    62.9    .045       0    78.8      .1       0
Bank Sta=62.9,78.8
XS Rating Curve= 0 ,0
Exp/Cntr=0.3,0.1

Type RM Length L Ch R = 1 ,9417.5  ,192.4,202.3,211.6
XS GIS Cut Line= 4
     1650965.147      574345.142     1650923.481      574414.586
     1650876.606      574492.711     1650819.314      574543.059
#Sta/Elev= 30
       0   840.5    49.4  838.14    65.2  837.91      77  836.72    88.9   836.6
    92.9  835.91    94.8  834.96    98.8  831.36   100.8  830.42   103.3  829.92
   112.7   828.7   114.7   828.9   116.6  831.08   118.3  834.24   120.6  836.74
   122.6  837.02   148.3  836.53   160.2   838.3   166.2  839.62   170.1  841.19
     178  845.41   195.6   853.5   199.5  855.98   203.4  859.53   207.3   863.5
   215.1  872.42   234.7  891.72   242.5  898.58   244.4  901.42   248.4  905.88
#Mann= 3 , 0 , 0
       0     .06       0   103.3    .045       0   118.3      .1       0
Bank Sta=103.3,118.3
XS Rating Curve= 0 ,0
Exp/Cntr=0.3,0.1

Type RM Length L Ch R = 1 ,9215.2  ,289.8,291.9,293.8
XS GIS Cut Line= 3
     1650899.175      574218.406     1650791.536      574280.906
     1650663.064      574371.184
#Sta/Elev= 30
       0  844.18       4  843.05    11.8  839.85    15.8  839.19    27.7  838.98
    49.4  837.43    63.2  835.71    75.1  835.83   130.4  833.95   132.4  833.51
   134.4  831.02   136.4  827.27   138.4  825.67   140.4  825.65   148.3  826.62
   151.5   830.2   152.3  831.25   154.3  832.88   156.3  833.38   184.1  833.66
   190.1  835.11     196  838.42     206  846.97   213.9   855.6   215.9  857.42
   229.8  867.79   249.7  879.61   263.6  886.61   273.5  893.06   281.5  896.89
#Mann= 3 , 0 , 0
       0     .06       0   134.4    .045       0   151.5      .1       0
Bank Sta=134.4,151.5
XS Rating Curve= 0 ,0
Exp/Cntr=0.3,0.1

Type RM Length L Ch R = 1 ,8923.4  ,312.2,313.9,315.3
XS GIS Cut Line= 3
     1650772.439      573959.725     1650583.203      574067.364
     1650491.189      574112.503
#Sta/Elev= 30
       0  847.42      20  837.35      30  833.79      38  830.48      40  830.12
    45.9   829.4    63.9  828.95   121.8  828.94   125.8  828.05   127.8  827.14
   131.8  824.63   135.1   823.7   145.8  821.84   147.8  822.36   149.8  824.49
   151.8  826.63   153.8   827.9   157.8  829.36   167.8  829.55   181.8  829.02
   183.8  829.56   187.8  831.32   189.7  831.66   205.7  832.97   211.7  833.88
   229.5   842.5   274.9  857.66   282.8   861.2   304.4   872.3   320.2   879.1
#Mann= 3 , 0 , 0
       0      .1       0   135.1    .045       0   149.8      .1       0
#XS Ineff= 2 , 0
          115.94  840.51
Permanent Ineff=
       F       F
Bank Sta=135.1,149.8
XS Rating Curve= 0 ,0
Exp/Cntr=0.3,0.1

Type RM Length L Ch R = 1 ,8609.5  ,323.5,320.7,317.4
XS GIS Cut Line= 4
     1650610.981      573695.836      1650531.12      573739.239
     1650444.314      573780.906     1650350.564      573838.198
#Sta/Elev= 30
       0  847.66    21.7  840.89    53.4  831.57    63.2  830.35    69.2   828.6
      79  826.84    88.9  825.94    96.8  824.83   106.6  824.14   108.6  823.64
   116.4  820.18   119.5  819.26   134.1  818.28   134.5  818.31   136.1  818.41
     142  822.14   145.9  823.64   159.7  824.49   171.5  824.33   187.2  828.06
   189.2  828.79   191.2  829.83   201.2  836.34   205.2  839.23   253.1  865.97
   259.1   869.9   269.1  877.08   277.1  881.89   289.1  890.12     297  894.95
#Mann= 3 , 0 , 0
       0      .1       0   119.5    .045       0   134.5     .08       0
Bank Sta=119.5,134.5
XS Rating Curve= 0 ,0
Exp/Cntr=0.3,0.1

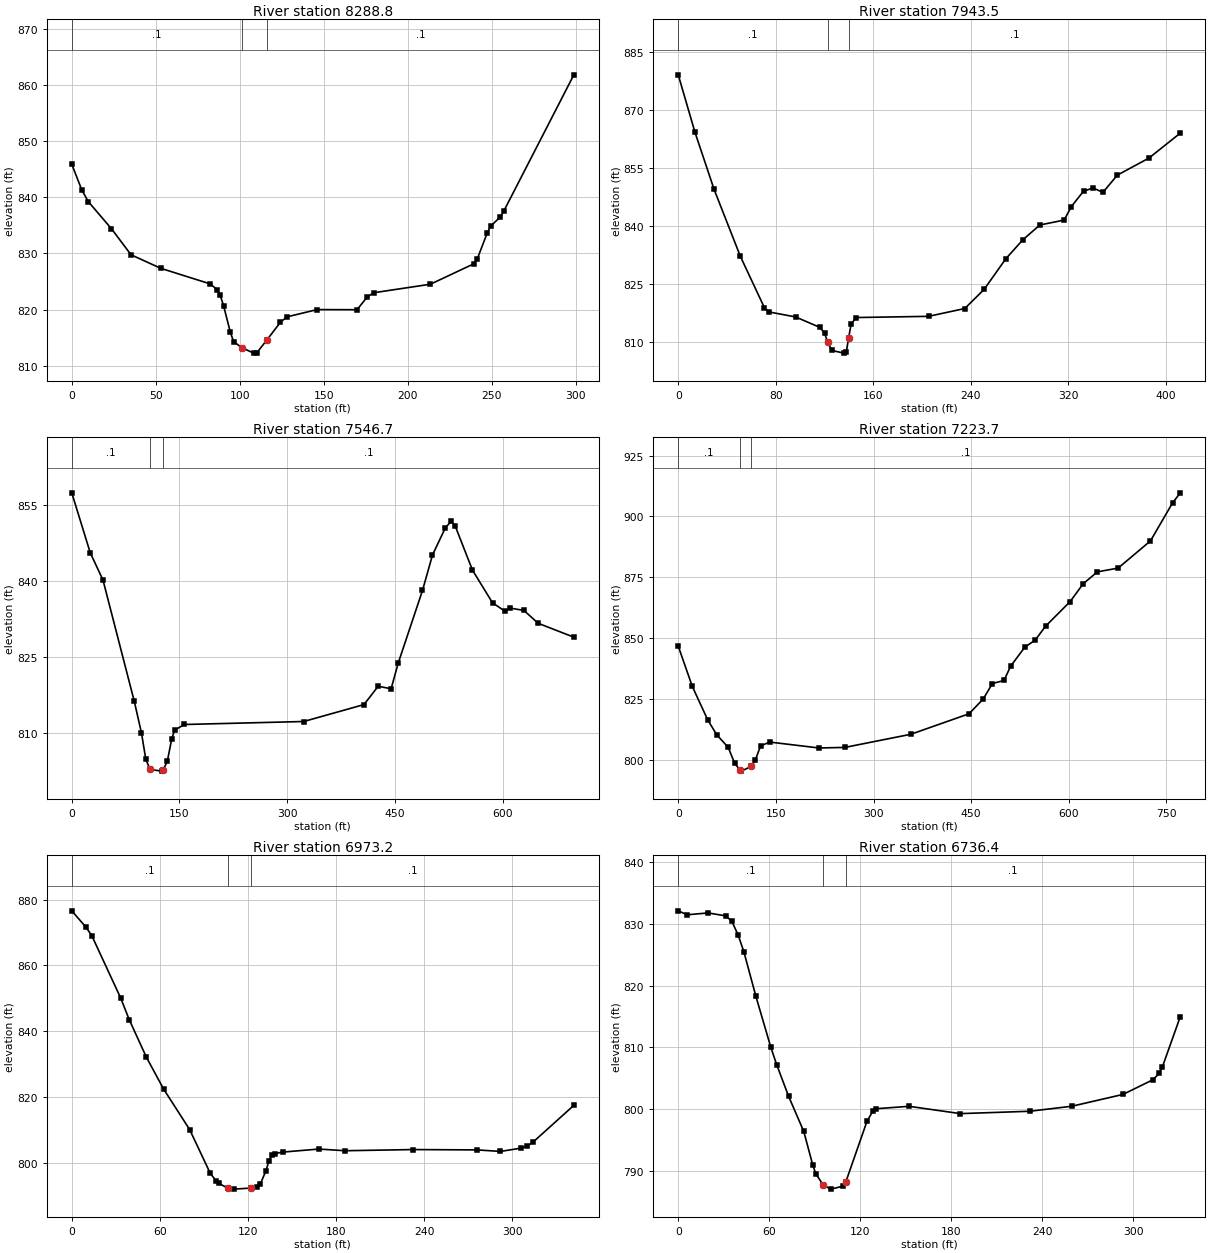
Type RM Length L Ch R = 1 ,8288.8  ,344,345.3,346.5
XS GIS Cut Line= 3
     1650423.481      573388.545     1650378.342      573452.781
     1650194.314      573574.309
#Sta/Elev= 30
       0  845.87     5.9  841.34     9.8  839.23    23.6   834.4    35.3  829.75
      53  827.34    82.5  824.56    86.5  823.56    88.4  822.53    90.4  820.69
    94.4  815.98    96.4  814.29   101.1  813.24   108.3  812.24   110.3  812.35
   116.1  814.54   124.2  817.72   128.2   818.7   146.1  819.99   169.9  819.97
   175.9  822.22   179.8  822.99   213.6  824.51   239.4  828.14   241.4  828.94
   247.4  833.62   249.4  834.83   255.3  836.52   257.3  837.54     299  861.79
#Mann= 3 , 0 , 0
       0      .1       0   101.1    .045       0   116.1      .1       0
Bank Sta=101.1,116.1
XS Rating Curve= 0 ,0
Exp/Cntr=0.3,0.1

Type RM Length L Ch R = 1 ,7943.5  ,401.5,396.8,391.6
XS GIS Cut Line= 4
     1650244.661      573124.656     1650173.481      573180.211
     1650048.481      573253.128     1649926.953        573381.6
#Sta/Elev= 30
       0  879.07    13.7  864.23    29.4  849.43      51  832.06    70.7  818.79
    74.6   817.7    96.2  816.42   116.1  813.72     120  812.23   122.5  809.97
     126  807.74   135.9  807.05   137.9  807.47   139.8  811.05   141.8  814.54
   145.8  816.26   205.3  816.57     235  818.59   250.9  823.55   268.8  831.52
   282.7  836.39   296.6  840.21   316.5  841.48   322.4  844.96   332.4  848.96
   340.3  849.79   348.3  848.65   360.2  853.12     386  857.51   411.8  863.99
#Mann= 3 , 0 , 0
       0      .1       0   122.5    .045       0   139.8      .1       0
Bank Sta=122.5,139.8
XS Rating Curve= 0 ,0
Exp/Cntr=0.3,0.1

Type RM Length L Ch R = 1 ,7546.7  ,318.2,323,327.4
XS GIS Cut Line= 4
     1650065.842      572793.059     1649985.981      572827.781
      1649749.87      573046.531      1649531.12      573237.503
#Sta/Elev= 30
       0   857.5    25.7  845.65    43.5  840.23    87.1  816.21    97.1  809.97
   103.1  804.77   109.1  802.75   125.1  802.42   127.1  802.59   133.1   804.4
   139.1   808.7   143.1  810.53     157  811.65     323  812.24     407  815.59
   426.8  819.22   444.8  818.72   454.7  823.81   488.5  838.18   502.4  845.19
   520.3  850.56   528.3  851.86   534.2  850.88   558.1   842.2     586  835.74
   603.9  834.02   609.8   834.7   629.7  834.23   649.6  831.68   699.3  828.93
#Mann= 3 , 0 , 0
       0      .1       0   109.1    .045       0   127.1      .1       0
Bank Sta=109.1,127.1
XS Rating Curve= 0 ,0
Exp/Cntr=0.3,0.1

Type RM Length L Ch R = 1 ,7223.7  ,249,250.5,251.4
XS GIS Cut Line= 4
     1649885.286      572517.017     1649827.995      572555.211
     1649569.314      572711.461     1649291.536      572999.656
#Sta/Elev= 30
       0  846.68    21.6  830.14    45.2  816.44      59  810.32    76.8  805.06
    86.8  798.48    94.7  795.88    96.7  795.32   112.5  797.27   118.6  800.02
   126.5  805.67   140.4  807.27     216  804.84   255.8  805.06   357.2  810.46
   446.7  818.89   468.6     825   482.6  831.32   500.5  832.58   510.5   838.4
   532.4  846.28   548.3  849.15   564.2  854.86   602.1  865.02     622   872.3
   643.9  877.23   675.8  878.77   725.5  889.96   759.4  905.59   771.3  909.71
#Mann= 3 , 0 , 0
       0      .1       0    94.7    .045       0   112.5      .1       0
Bank Sta=94.7,112.5
XS Rating Curve= 0 ,0
Exp/Cntr=0.3,0.1

Type RM Length L Ch R = 1 ,6973.2  ,235,236.8,238.1
XS GIS Cut Line= 3
     1649772.439      572320.836     1649699.522      572343.406
     1649465.147      572468.406
#Sta/Elev= 30
       0  876.57     9.8  871.53    13.7  868.96    33.3   850.1    39.1  843.54
    50.9  832.02    62.6  822.38    80.3   810.1    94.3  796.84    98.3  794.53
   100.3  793.73   106.2   792.3   110.3     792   122.3  792.33   126.3  792.53
   128.3  793.45   132.2  797.48   134.2  800.41   136.2  802.23   138.2  802.82
   144.2  803.27   168.2  804.18   186.2  803.67   232.1  804.02     276  803.92
     292  803.46     306  804.45     310  805.08     314   806.2     342  817.46
#Mann= 3 , 0 , 0
       0      .1       0   106.2    .045       0   122.3      .1       0
Bank Sta=106.2,122.3
XS Rating Curve= 0 ,0
Exp/Cntr=0.3,0.1

Type RM Length L Ch R = 1 ,6736.4  ,272.1,274.8,277.3
XS GIS Cut Line= 3
     1649666.536      572112.503     1649598.828      572133.336
     1649360.981      572239.239
#Sta/Elev= 30
       0  832.06     5.9  831.42    19.7  831.72    31.5  831.24    35.4  830.34
    39.4  828.23    43.3  825.45    51.2  818.28      61  810.09    64.9  807.25
    72.8  802.12    82.8  796.45    88.7  791.06    90.7  789.63    95.6   787.8
   100.6  787.13   108.6   787.6   110.6  788.33   124.5  798.08   128.5  799.77
   130.5  800.11   152.3   800.5   186.1  799.32   231.8   799.7   259.6  800.51
   293.4  802.42   313.3  804.81   317.3  805.83   319.3  806.81   331.2  814.99
#Mann= 3 , 0 , 0
       0      .1       0    95.6    .045       0   110.6      .1       0
Bank Sta=95.6,110.6
XS Rating Curve= 0 ,0
Exp/Cntr=0.3,0.1

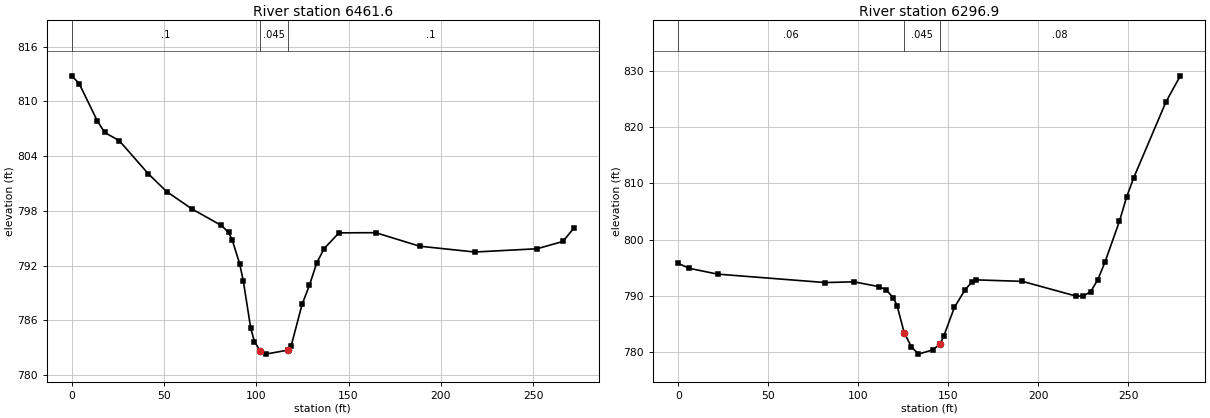
Type RM Length L Ch R = 1 ,6461.6  ,164.1,164.7,164.7
XS GIS Cut Line= 3
     1649604.036      571886.809     1649524.175       571872.92
     1649341.883      571930.211
#Sta/Elev= 30
       0   812.8       4  811.95    13.8  807.88    17.8  806.59    25.7   805.7
    41.5  802.06    51.4  800.12    65.2   798.2    81.1   796.4      85  795.64
      87  794.78      91   792.2      93  790.27      97  785.13      99  783.68
   102.2  782.63     105   782.3   117.2  782.74   118.9  783.21   124.8  787.74
   128.8  789.84   132.8  792.32   136.8  793.87   144.8  795.59   164.7  795.61
   188.5  794.13   218.4  793.49   252.2  793.85   266.2  794.65   272.1  796.12
#Mann= 3 , 0 , 0
       0      .1       0   102.2    .045       0   117.2      .1       0
Bank Sta=102.2,117.2
XS Rating Curve= 0 ,0
Exp/Cntr=0.3,0.1

Type RM Length L Ch R = 1 ,6296.9  ,35.8,35.8,35.8
XS GIS Cut Line= 2
     1649574.522      571687.156     1649307.161      571767.017
#Sta/Elev= 30
       0  795.77       6  794.89    21.9  793.85    81.7  792.35    97.7  792.48
   111.6  791.62   115.6  791.06   119.6  789.59   121.6  788.26   125.6  783.38
   129.6   780.9   133.5  779.61   141.5  780.38   145.5   781.4   147.5  782.78
   153.5  787.96   159.4  791.06   163.4  792.52   165.4  792.83   191.3  792.56
   221.2  789.93   225.2  789.96   229.2  790.74   233.2  792.88   237.2  796.05
   245.2  803.29   249.1  807.51   253.1  811.01   271.1  824.56     279  829.15
#Mann= 3 , 0 , 0
       0     .06       0   125.6    .045       0   145.5     .08       0
Bank Sta=125.6,145.5
XS Rating Curve= 0 ,0
Exp/Cntr=0.3,0.1