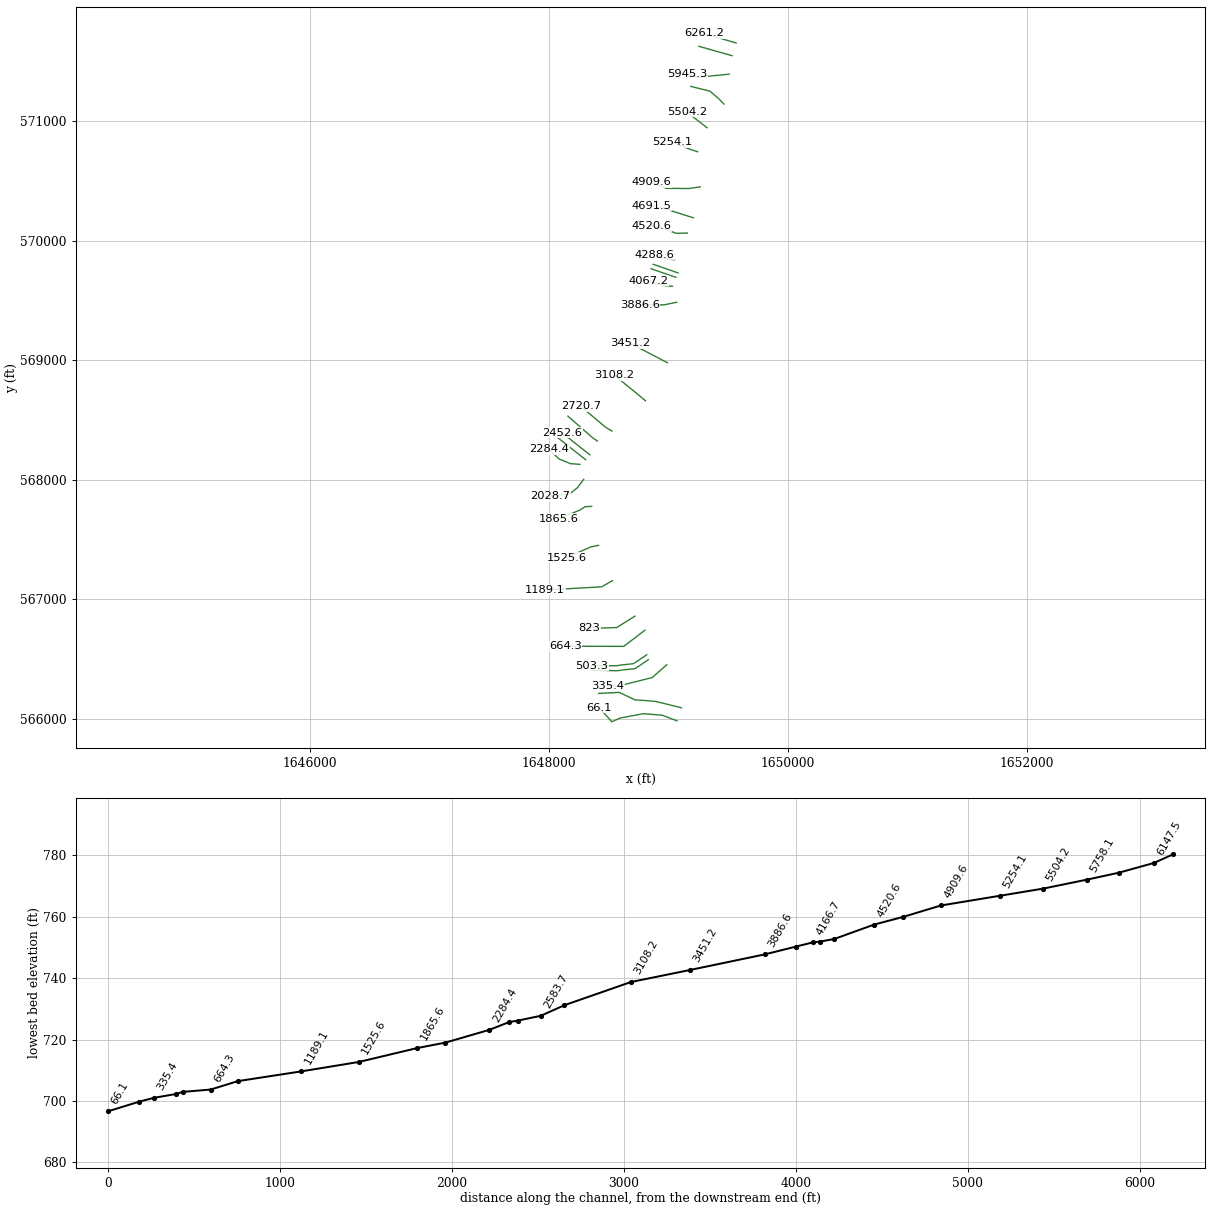
HEC-RAS study PETERSRUN.prj: PETERSRUN

--- PETERSRUN.g01 (geometry) --- (continued)

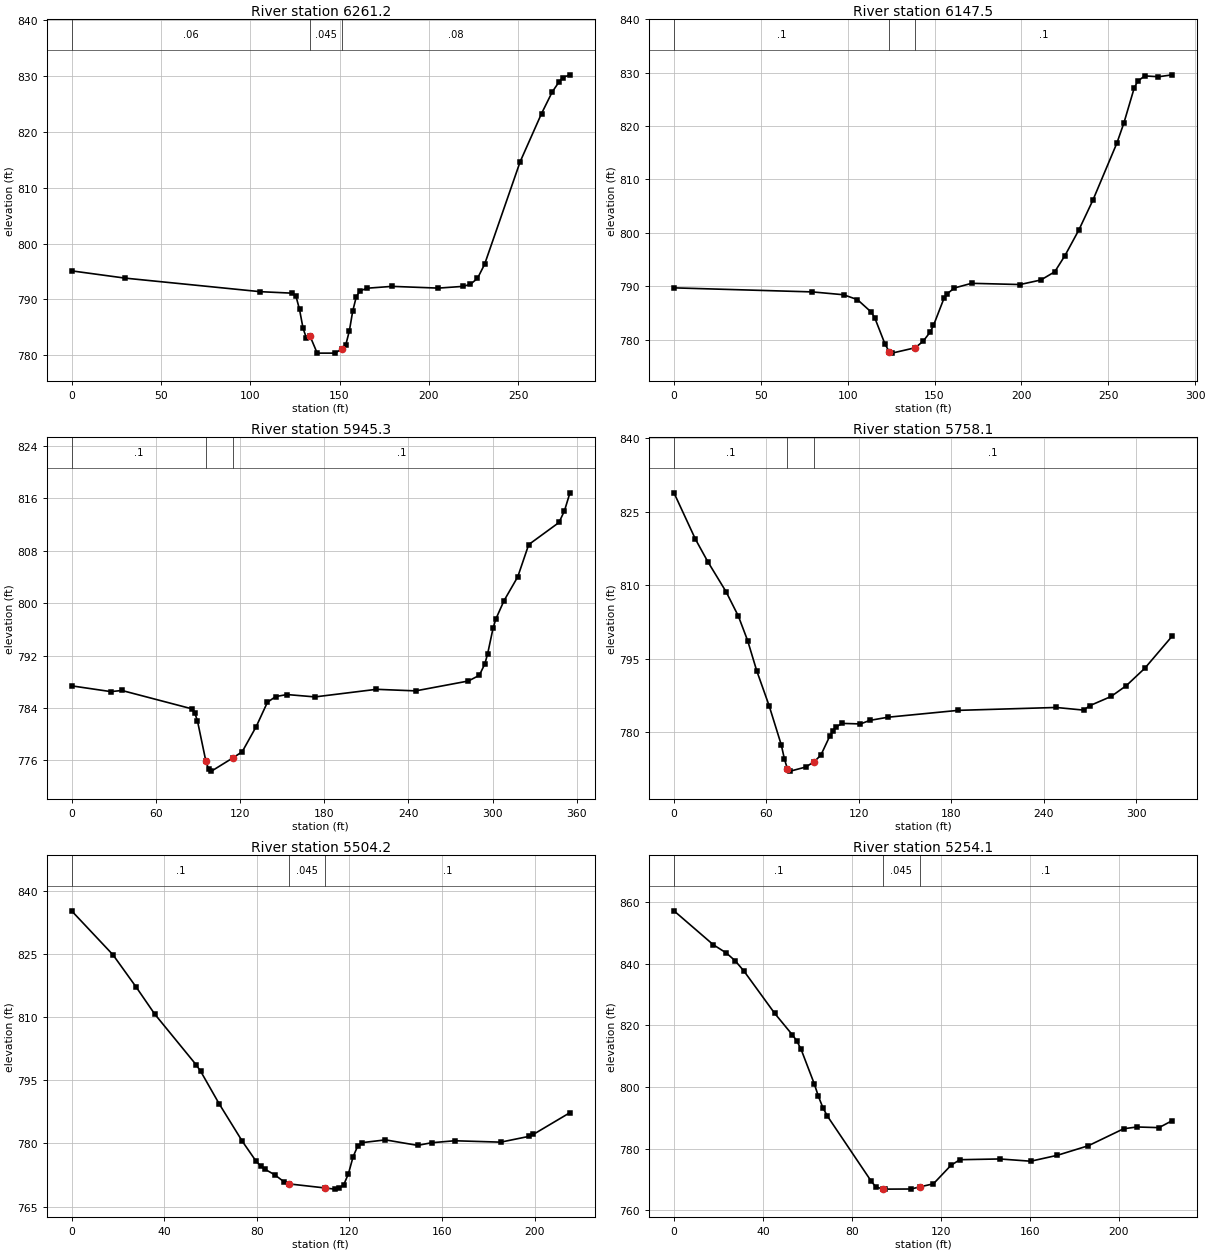
Type RM Length L Ch R = 1 ,6261.2  ,113.1,113.7,113.7
XS GIS Cut Line= 2
     1649565.842      571652.434     1649298.481      571732.295
#Sta/Elev= 30
       0   795.1    29.9   793.8   105.6  791.37   123.6   791.1   125.6  790.57
   127.6  788.19   129.6  784.78   131.5  783.06   133.5   783.4   137.5  780.36
   147.5  780.36   151.5  781.16   153.5  781.83   155.5  784.34   157.4  787.91
   159.4  790.47   161.4  791.49   165.4  791.99   179.4  792.32   205.3  792.01
   219.2  792.32   223.2  792.68   227.2  793.74   231.2  796.26   251.1  814.64
   263.1  823.29   269.1  827.17     273     829     275  829.74     279  830.22
#Mann= 3 , 0 , 0
       0     .06       0   133.5    .045       0   151.5     .08       0
Bank Sta=133.5,151.5
XS Rating Curve= 0 ,0
Exp/Cntr=0.3,0.1

Type RM Length L Ch R = 1 ,6147.5  ,193.4,202.2,210.3
XS GIS Cut Line= 2
      1649531.12      571546.531     1649255.078      571624.656
#Sta/Elev= 30
       0  789.71    79.7  788.95    97.6  788.42   105.6  787.51   113.6  785.16
   115.6  784.09   121.5  779.17   123.9 777.762   125.5  777.49   138.9 778.498
   143.4   779.7   147.4  781.39   149.4  782.68   155.4  787.72   157.4  788.63
   161.4  789.68   171.3  790.56   199.2  790.33   211.2  791.18   219.2  792.72
   225.1  795.76   233.1  800.56   241.1  806.08     255  816.83     259  820.57
     265  827.18     267   828.4     271  829.39   278.9  829.23   286.9  829.59
#Mann= 3 , 0 , 0
       0      .1       0   123.9    .045       0   138.9      .1       0
Bank Sta=123.9,138.9
XS Rating Curve= 0 ,0
Exp/Cntr=0.3,0.1

Type RM Length L Ch R = 1 ,5945.3  ,204.6,187.2,167.8
XS GIS Cut Line= 3
      1649508.55      571392.017     1649244.661      571365.975
     1649159.592      571395.489
#Sta/Elev= 30
       0  787.37    27.9  786.49    35.9  786.66    85.7  783.86    87.7  783.29
    89.7  782.03    95.7  775.87    97.7  774.61    99.7  774.34   115.1  776.38
   121.6   777.3   131.6  781.15   139.6  784.87   145.5  785.73   153.5  786.04
   173.5  785.68   217.3  786.84   245.2   786.6   282.8  788.11   290.6  788.98
   294.5   790.7   296.5  792.24   300.4  796.18   302.4  797.59   308.2  800.38
     318  804.03   325.8  808.95   347.4  812.33   351.3  814.13   355.2  816.86
#Mann= 3 , 0 , 0
       0      .1       0    95.7    .045       0   115.1      .1       0
Bank Sta=95.7,115.1
XS Rating Curve= 0 ,0
Exp/Cntr=0.3,0.1

Type RM Length L Ch R = 1 ,5758.1  ,252.6,253.9,255
XS GIS Cut Line= 4
     1649463.411      571142.017     1649423.481      571183.684
     1649347.092      571249.656      1649187.37      571289.586
#Sta/Elev= 30
       0  828.85    13.9   819.4    21.9  814.82    33.8  808.67    41.8  803.67
    47.8  798.68    53.7  792.52    61.7  785.43    69.6  777.43    71.6  774.61
    73.5  772.59    75.5  772.06    85.4  772.89    90.9  773.96    95.3  775.33
   101.2  779.29   103.2  780.33   105.2   781.1   109.2   781.8     121  781.69
     127  782.41   138.8  783.06   184.4  784.46   247.9  785.05   265.8  784.51
   269.7  785.41   283.6   787.3   293.5  789.52   305.4  793.04   323.3  799.65
#Mann= 3 , 0 , 0
       0      .1       0    73.5    .045       0    90.9      .1       0
Bank Sta=73.5,90.9
XS Rating Curve= 0 ,0
Exp/Cntr=0.3,0.1

Type RM Length L Ch R = 1 ,5504.2  ,243.5,250.1,256.4
XS GIS Cut Line= 2
     1649322.786        570944.1     1649152.647      571076.045
#Sta/Elev= 30
       0  835.32    17.9  824.85    27.9  817.19    35.9  810.78    53.8  798.72
    55.8  797.13    63.8  789.39    73.8  780.49    79.7  775.79    81.7  774.64
    83.7  773.82    87.7  772.58    91.7  770.92      94  770.39   109.6  769.42
   113.6  769.15   115.6  769.33   117.6  770.23   119.6  772.81   121.6  776.81
   123.6  779.39   125.6  780.21   135.6  780.86   149.5  779.55   155.5  780.18
   165.5  780.65   185.4  780.32   197.4  781.67   199.4  782.14   215.3  787.33
#Mann= 3 , 0 , 0
       0      .1       0      94    .045       0   109.6      .1       0
Bank Sta=94,109.6
XS Rating Curve= 0 ,0
Exp/Cntr=0.3,0.1

Type RM Length L Ch R = 1 ,5254.1  ,336.1,344.5,352.6
XS GIS Cut Line= 3
     1649244.661      570742.711     1649171.745      570767.017
     1649034.592      570820.836
#Sta/Elev= 30
       0  857.16    17.7  846.15    23.6  843.45    27.6   840.9    31.5  837.59
    45.3  823.89    53.2  816.96    55.2  815.02    57.2  812.17    63.1  801.04
      65   796.9      67  793.25      69  790.55    88.8  769.34    90.8  767.56
    93.9  766.86    94.8  766.83   106.7  766.87   110.7  767.58   116.7  768.55
   124.6  774.55   128.6  776.38   146.6  776.62   160.5  775.89   172.4   777.8
   186.4  780.91   202.3  786.43   208.3     787   218.2  786.79   224.2  789.08
#Mann= 3 , 0 , 0
       0      .1       0    93.9    .045       0   110.7      .1       0
Bank Sta=93.9,110.7
XS Rating Curve= 0 ,0
Exp/Cntr=0.3,0.1

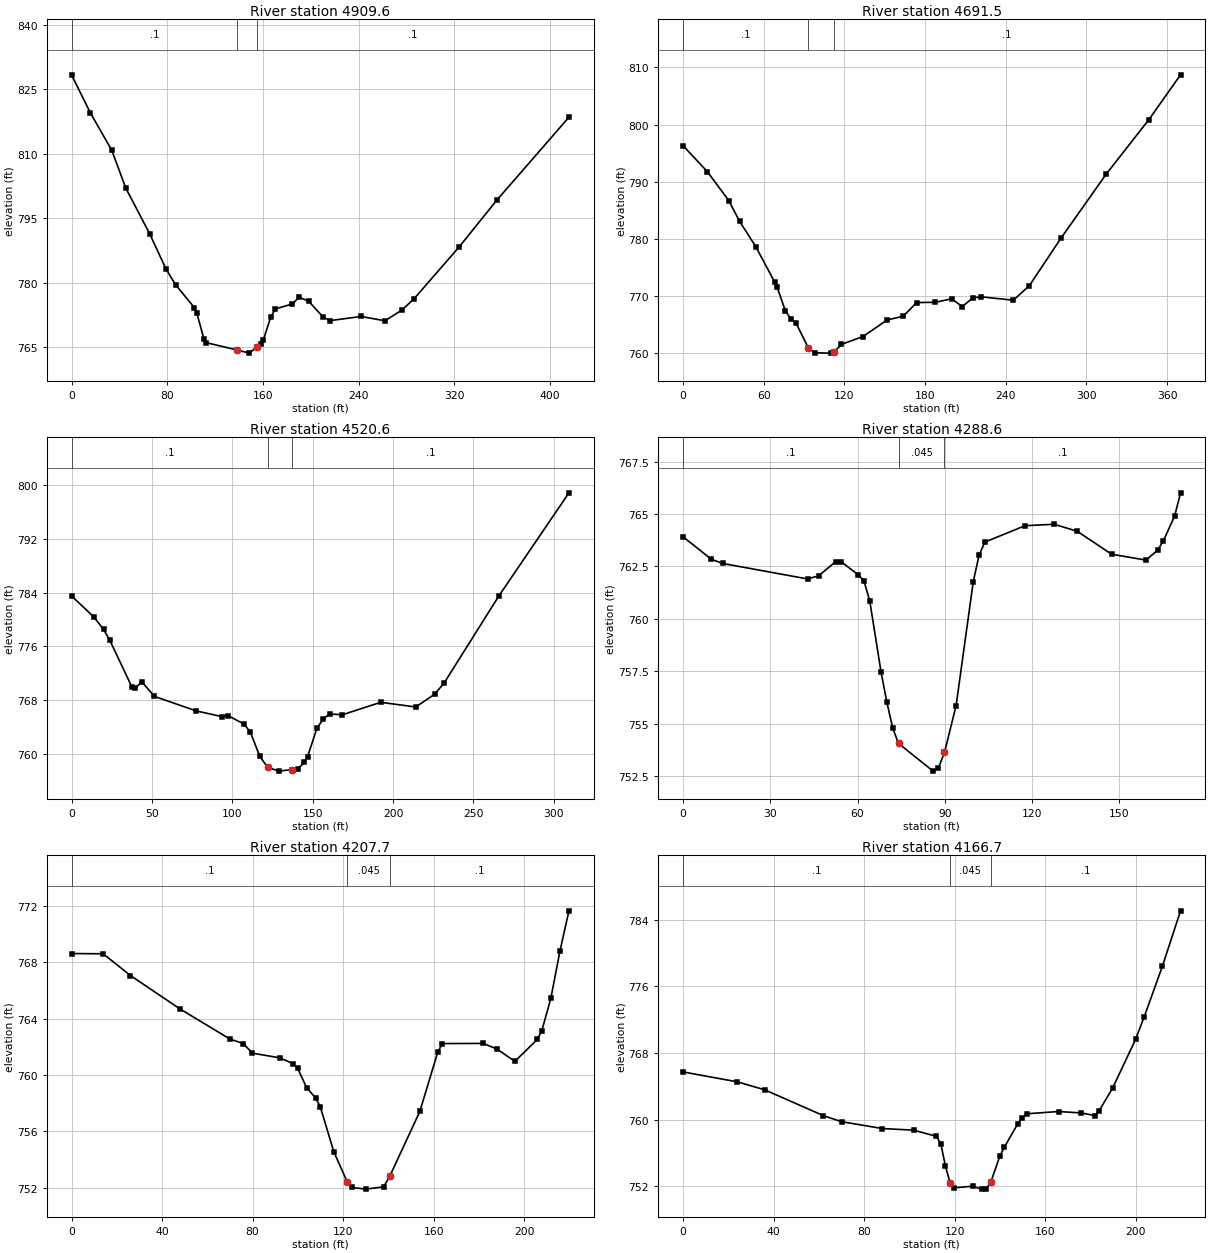
Type RM Length L Ch R = 1 ,4909.6  ,224.3,218.1,210.9
XS GIS Cut Line= 4
     1649265.495      570449.309     1649171.745       570435.42
     1648980.772      570437.156     1648860.981      570487.503
#Sta/Elev= 30
       0  828.35    15.8  819.47    33.6  810.82    45.4  801.98    65.2  791.45
      79  783.18    86.9  779.56   102.7  774.23   104.7  772.94   110.7   766.9
   112.7  766.07   138.5  764.38   148.5  763.65     155  765.09   158.4  765.67
   160.4  766.81   166.4  771.97   170.4  773.94   184.3  775.06   190.3  776.65
   198.2   775.7   210.2  772.06   216.1  771.21     242  772.17   261.9  771.17
   275.8  773.61   285.8  776.15   323.7  788.26   355.7  799.31   415.7   818.5
#Mann= 3 , 0 , 0
       0      .1       0   138.5    .045       0     155      .1       0
Bank Sta=138.5,155
XS Rating Curve= 0 ,0
Exp/Cntr=0.3,0.1

Type RM Length L Ch R = 1 ,4691.5  ,172.2,170.9,169.5
XS GIS Cut Line= 4
     1649209.627      570191.085     1649144.522      570210.617
     1648960.061       570269.21     1648853.724      570290.912
#Sta/Elev= 30
       0  796.28      18  791.75      34  786.66      42  783.04      54  778.63
      68  772.44      70  771.48      76  767.39    79.9  766.02    83.9  765.25
    93.2  760.84    97.9  760.01   109.9  759.96   111.9  760.08   117.8  761.49
   133.8  762.87   151.8  765.77   163.8  766.43   173.7  768.82   187.7  768.86
   199.7  769.48   207.6  768.12   215.6  769.64   221.6  769.82   245.6  769.23
   257.5  771.76   281.2  780.14   314.8  791.34   346.4  800.84     370   808.7
#Mann= 3 , 0 , 0
       0      .1       0    93.2    .045       0   111.9      .1       0
Bank Sta=93.2,111.9
XS Rating Curve= 0 ,0
Exp/Cntr=0.3,0.1

Type RM Length L Ch R = 1 ,4520.6  ,229.9,232.1,232.9
XS GIS Cut Line= 4
     1649157.543      570063.047     1649064.227      570060.877
     1648940.529       570108.62     1648858.064      570121.641
#Sta/Elev= 30
       0  783.52    13.9  780.38    19.9  778.54    23.8  776.92    37.7  769.88
    39.7  769.82    43.7  770.72    51.6  768.55    77.4   766.4    93.3  765.55
    97.3   765.7   107.2  764.44   111.2  763.25   117.1  759.63     122  757.98
     129  757.42     137  757.65   140.8  757.78   144.8  758.71   146.8  759.58
   152.7  763.84   156.7  765.22   160.6  765.93   168.5  765.82   192.3  767.67
   214.1  766.98   225.9  768.88   231.9   770.6   265.7  783.48   309.4  798.88
#Mann= 3 , 0 , 0
       0      .1       0     122    .045       0     137      .1       0
Bank Sta=122,137
XS Rating Curve= 0 ,0
Exp/Cntr=0.3,0.1

Type RM Length L Ch R = 1 ,4288.6  ,82.2,80.9,80.6
XS GIS Cut Line= 3
     1649051.467      569839.262     1648989.661      569846.207
     1648886.189      569880.235
#Sta/Elev= 30
       0  763.91     9.7  762.84    13.6  762.64    42.8   761.9    46.6  762.05
    52.5  762.73    54.4  762.72    60.2   762.1    62.2  761.81    64.2  760.85
    68.1  757.44    70.1  756.01    72.1  754.78    74.1  754.05      86  752.73
    87.8  752.88    89.9  753.62    93.9  755.86    99.8  761.77   101.8  763.04
   103.8  763.66   117.6  764.44   127.6  764.51   135.5  764.18   147.4  763.08
   159.2   762.8   163.2  763.27   165.2  763.72   169.1  764.92   171.1  766.01
#Mann= 3 , 0 , 0
       0      .1       0    74.1    .045       0    89.9      .1       0
Bank Sta=74.1,89.9
XS Rating Curve= 0 ,0
Exp/Cntr=0.3,0.1

Type RM Length L Ch R = 1 ,4207.7  ,41,41,41
XS GIS Cut Line= 2
     1649080.633       569729.54     1648872.995      569801.762
#Sta/Elev= 30
       0  768.62      14   768.6      26  767.06      48  764.68      70  762.55
    75.9  762.23    79.9  761.55    91.9  761.22    97.9  760.81    99.9  760.47
   103.9   759.1   107.9  758.36   109.9  757.75   115.9  754.55   121.9  752.38
   123.9  752.02   129.9   751.9   137.9  752.06   140.6  752.81   153.9  757.41
   161.9  761.66   163.9  762.23   181.9  762.24   187.9  761.85   195.9  760.97
   205.8  762.52   207.8  763.14   211.8  765.44   215.8  768.78   219.8  771.65
#Mann= 3 , 0 , 0
       0      .1       0   121.9    .045       0   140.6      .1       0
Bank Sta=121.9,140.6
XS Rating Curve= 0 ,0
Exp/Cntr=0.3,0.1

Type RM Length L Ch R = 1 ,4166.7  ,98.3,99.5,100.8
XS GIS Cut Line= 2
     1649061.883      569692.735     1648854.245      569764.957
#Sta/Elev= 30
       0  765.73      24  764.54      36  763.59      62  760.48      70  759.76
    87.9  758.94   101.9  758.74   111.9     758   113.9  757.08   115.9  754.43
     118  752.39   119.9  751.82   127.9  752.01   131.9  751.66   133.9  751.71
   135.9  752.46   139.9  755.59   141.9  756.69   147.9  759.51   149.9  760.25
   151.9  760.71   165.9  760.98   175.9  760.81   181.9   760.5   183.9   761.1
   189.9  763.86   199.9  769.63   203.8  772.39   211.8  778.44   219.8  785.08
#Mann= 3 , 0 , 0
       0      .1       0     118    .045       0   135.9      .1       0
Bank Sta=118,135.9
XS Rating Curve= 0 ,0
Exp/Cntr=0.3,0.1

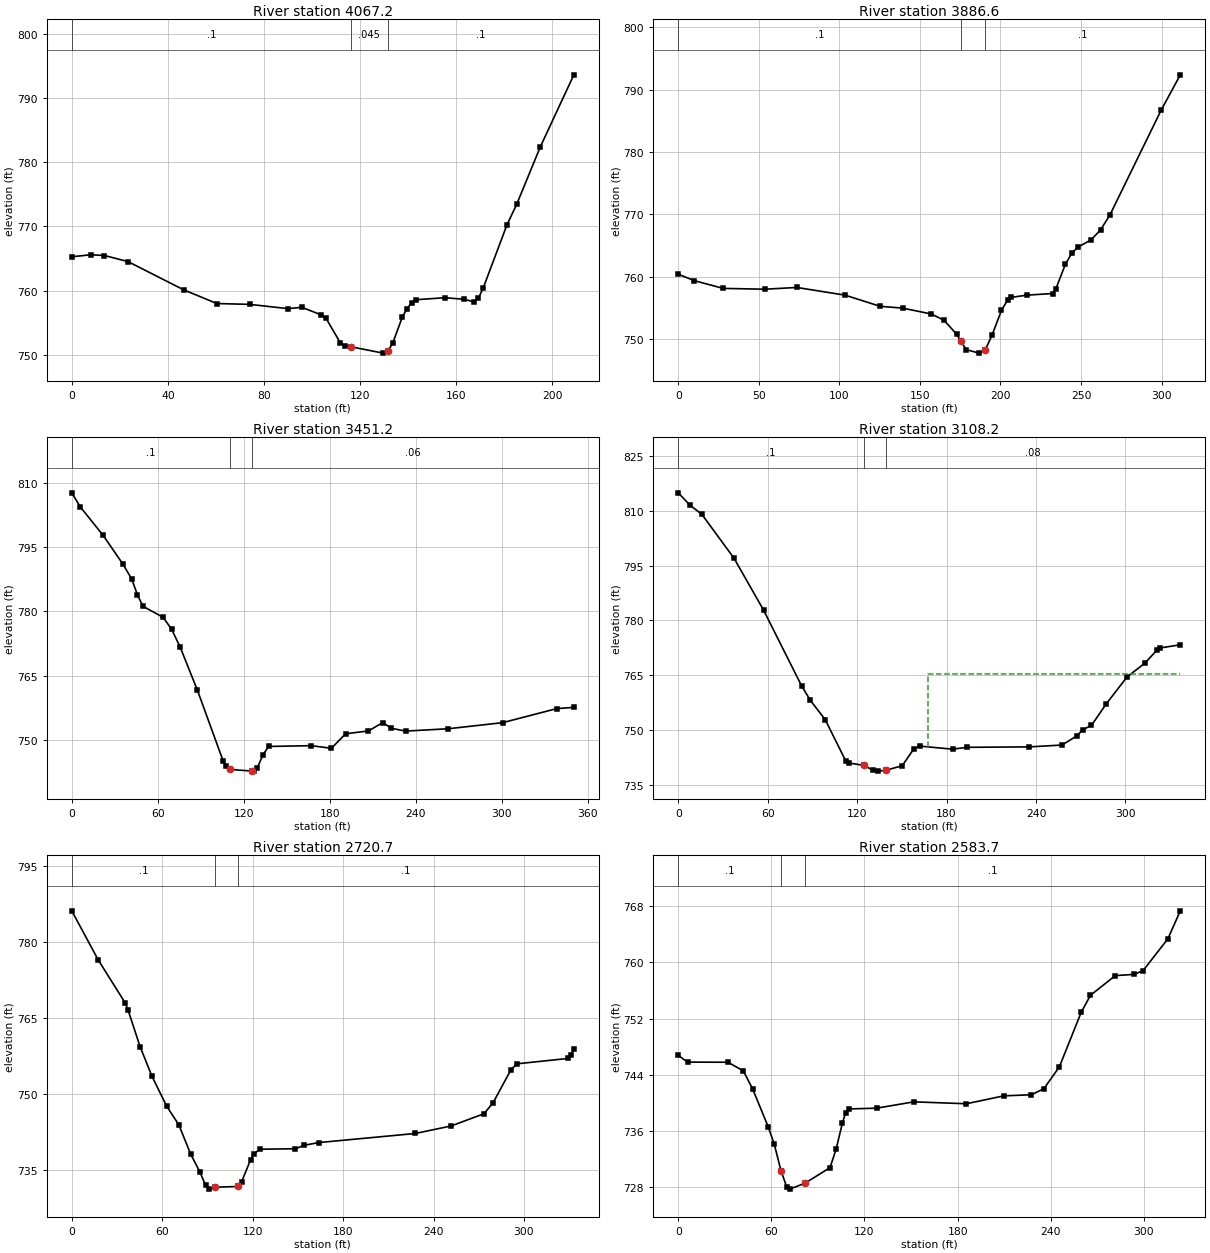
Type RM Length L Ch R = 1 ,4067.2  ,174,180.6,186.8
XS GIS Cut Line= 3
     1649033.411      569617.409     1648961.797      569625.222
     1648830.286      569662.982
#Sta/Elev= 30
       0  765.27     7.8  765.58    13.6  765.47    23.4  764.52    46.7   760.1
    60.4  757.99      74  757.86    89.9   757.2    95.8   757.4   103.8  756.22
   105.8  755.69   111.7   751.9   113.7  751.42   116.2  751.25   129.6  750.27
   131.5   750.6   133.5  751.78   137.5  755.86   139.5  757.21   141.4  758.12
   143.4  758.59   155.3   758.9   163.3  758.65   167.2  758.26   169.2  758.82
   171.2  760.42   181.1  770.27   185.1  773.42     195  782.43   208.9   793.6
#Mann= 3 , 0 , 0
       0      .1       0   116.2    .045       0   131.5      .1       0
Bank Sta=116.2,131.5
XS Rating Curve= 0 ,0
Exp/Cntr=0.3,0.1

Type RM Length L Ch R = 1 ,3886.6  ,446.2,435.4,424.5
XS GIS Cut Line= 3
     1649069.713      569484.544     1648964.505      569462.669
     1648760.338      569462.149
#Sta/Elev= 30
       0   760.4      10  759.36    27.9  758.12    53.7  757.99    73.6  758.27
   103.5  757.04   125.3  755.25   139.2  754.96     157  754.02   164.9  753.02
   172.9  750.74   175.4  749.62   178.8  748.29   186.8  747.74   190.4  748.17
   194.7  750.59   200.6  754.59   204.6  756.33   206.6  756.68   216.5  757.04
   232.3   757.3   234.3  758.01   240.3     762   244.2  763.76   248.2  764.77
   256.1  765.88   262.1   767.5     268  769.94   299.7   786.7   311.6  792.37
#Mann= 3 , 0 , 0
       0      .1       0   175.4    .045       0   190.4      .1       0
Bank Sta=175.4,190.4
XS Rating Curve= 0 ,0
Exp/Cntr=0.3,0.1

Type RM Length L Ch R = 1 ,3451.2  ,347.6,343.1,338.5
XS GIS Cut Line= 2
     1648990.026      568979.544     1648679.262      569141.003
#Sta/Elev= 30
       0  807.72       6  804.41    21.9  797.76    35.8  790.99    41.8  787.58
    45.8  783.87    49.7  781.18    63.7  778.62    69.6  775.84    75.6  771.66
    87.6  761.59   105.5  745.11   107.4  743.84   110.7  743.04   125.7  742.66
   127.4  742.65   129.3   743.3   133.3  746.43   137.3  748.42   167.1   748.6
   181.1  747.99     191  751.39   206.9  752.04   216.9     754   222.9  752.67
   232.8  752.01   262.6  752.56   300.5  753.98   338.3  757.27   350.2  757.56
#Mann= 3 , 0 , 0
       0      .1       0   110.7    .045       0   125.7     .06       0
Bank Sta=110.7,125.7
XS Rating Curve= 0 ,0
Exp/Cntr=0.3,0.1

Type RM Length L Ch R = 1 ,3108.2  ,387.4,387.5,386.5
XS GIS Cut Line= 3
     1648807.734        568660.1     1648740.026      568717.392
     1648547.318      568873.642
#Sta/Elev= 30
       0  814.94     7.9  811.55    15.8  809.07    37.4  797.04    57.2  782.86
    82.8  762.05    88.7  758.09    98.6  752.83   112.5  741.42   114.5  740.96
   124.3  740.34   130.4  739.06   134.3  738.74   139.3  738.98   150.2   740.2
   158.2  744.93   162.1  745.59     184  744.75   193.9  745.26   235.6  745.38
   257.4  745.88   267.3  748.36   271.3  750.07   277.2  751.26   287.2   757.2
   301.1  764.54     313   768.3   320.9  771.78   322.9  772.44   336.8  773.33
#Mann= 3 , 0 , 0
       0      .1       0   124.3    .045       0   139.3     .08       0
#XS Ineff= 2 , 0
                          167.71          765.28
Permanent Ineff=
       F       F
Bank Sta=124.3,139.3
XS Rating Curve= 0 ,0
Exp/Cntr=0.3,0.1

Type RM Length L Ch R = 1 ,2720.7  ,137,136.9,136.6
XS GIS Cut Line= 3
      1648528.22      568406.628     1648470.929       568441.35
     1648267.804      568613.225
#Sta/Elev= 30
       0  786.16    17.7  776.38    35.5  767.94    37.4   766.5    45.3  759.34
    53.2  753.48      63  747.54      71   743.9    78.9  738.09    84.9  734.63
    88.8  731.93    90.8  731.18    95.3  731.56   110.3   731.7   112.7  732.64
   118.6  736.96   120.6  738.07   124.6  739.06   148.4  739.16   154.4  739.86
   164.3  740.39   227.8  742.17   251.7  743.66   273.5  746.08   279.5  748.23
   291.4  754.78   295.4  755.94   329.1  756.99   331.1  757.62   333.1   758.8
#Mann= 3 , 0 , 0
       0      .1       0    95.3    .045       0   110.3      .1       0
Bank Sta=95.3,110.3
XS Rating Curve= 0 ,0
Exp/Cntr=0.3,0.1

Type RM Length L Ch R = 1 ,2583.7  ,130.3,131.1,132.1
XS GIS Cut Line= 3
     1648405.246      568323.005     1648360.107      568355.991
     1648158.718      568532.207
#Sta/Elev= 30
       0  746.76       6   745.8      32  745.78    41.9  744.56    47.9  742.01
    57.9  736.64    61.9  734.11    66.2  730.35    69.9  728.06    71.9  727.74
    81.9  728.61    97.8   730.8   101.8  733.47   105.8  737.17   107.8  738.56
   109.8  739.14   127.8  739.25   151.8  740.15   185.7  739.88   209.7     741
   227.6  741.16   235.6  742.02   245.6  745.14   259.6  752.86   265.6   755.3
   281.6   758.1   293.6  758.27   299.5   758.8   315.5  763.34   323.5  767.31
#Mann= 3 , 0 , 0
       0      .1       0    66.2    .045       0    81.9      .1       0
Bank Sta=66.2,81.9
XS Rating Curve= 0 ,0
Exp/Cntr=0.3,0.1

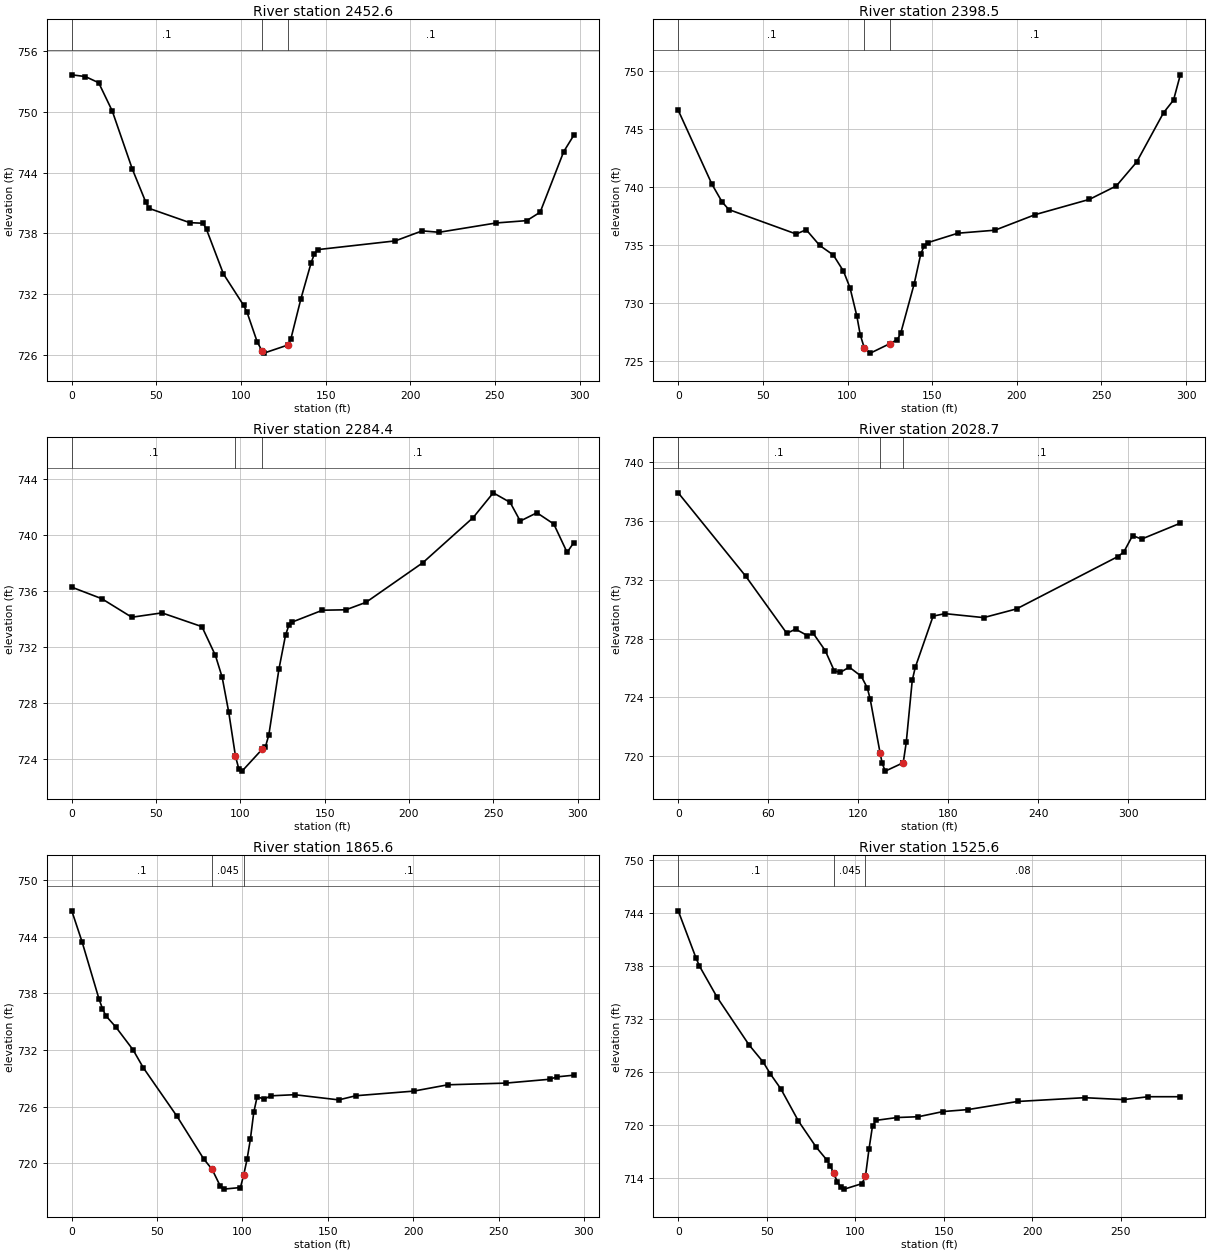
Type RM Length L Ch R = 1 ,2452.6  ,54.1,54.1,54.1
XS GIS Cut Line= 2
     1648342.746      568208.422     1648110.107       568392.45
#Sta/Elev= 30
       0  753.65       8  753.48    15.9  752.87    23.9  750.09    35.8  744.34
    43.8  741.06    45.8  740.47    69.7  739.07    77.6  739.01    79.6   738.4
    89.6  734.01   101.5  730.92   103.5  730.25   109.5  727.33   112.5  726.38
   113.5   726.2   127.5  726.99   129.4  727.58   135.4  731.58   141.4  735.11
   143.3  735.98   145.3  736.41   191.1  737.27     207  738.26     217  738.12
   250.8  739.04   268.8  739.27   276.7   740.1   290.6  746.07   296.6   747.7
#Mann= 3 , 0 , 0
       0      .1       0   112.5    .045       0   127.5      .1       0
Bank Sta=112.5,127.5
XS Rating Curve= 0 ,0
Exp/Cntr=0.3,0.1

Type RM Length L Ch R = 1 ,2398.5  ,107.5,114.1,120.3
XS GIS Cut Line= 2
     1648307.155      568167.623     1648074.517      568351.651
#Sta/Elev= 30
       0  746.63    19.9  740.25    25.9  738.72    29.9  738.06    69.7  735.95
    75.6  736.32    83.6  734.96    91.6  734.14    97.6  732.75   101.5   731.3
   105.5  728.88   107.5  727.27   109.9  726.12   113.5  725.67   124.9  726.48
   129.4  726.83   131.4  727.37   139.4  731.66   143.3  734.24   145.3  734.92
   147.3   735.2   165.2  736.02   187.1  736.28     211  737.63   242.9  738.94
   258.8   740.1   270.8  742.16   286.7  746.42   292.6  747.51   296.6  749.69
#Mann= 3 , 0 , 0
       0      .1       0   109.9    .045       0   124.9      .1       0
Bank Sta=109.9,124.9
XS Rating Curve= 0 ,0
Exp/Cntr=0.3,0.1

Type RM Length L Ch R = 1 ,2284.4  ,231.2,255.7,279.2
XS GIS Cut Line= 4
     1648259.412      568128.561     1648180.419      568134.637
     1648084.933        568173.7       1648001.6      568253.561
#Sta/Elev= 30
       0  736.26    17.8  735.44    35.6  734.12    53.5  734.43    77.2  733.45
    85.2   731.4    89.2  729.85    93.1  727.36    97.1  724.22    99.1  723.31
     101  723.16   113.1  724.74   114.9   724.9   116.9  725.75   122.9  730.44
   126.8  732.85   128.8  733.56   130.8  733.78   148.7  734.62   162.6  734.65
   174.5  735.18   208.3  738.01   238.1  741.22     250  742.98     260   742.3
     266  740.97   275.9  741.56   285.9  740.76   293.8  738.74   297.8  739.44
#Mann= 3 , 0 , 0
       0      .1       0    97.1    .045       0   113.1      .1       0
Bank Sta=97.1,113.1
XS Rating Curve= 0 ,0
Exp/Cntr=0.3,0.1

Type RM Length L Ch R = 1 ,2028.7  ,165.7,163.1,160.3
XS GIS Cut Line= 4
      1648291.53      568003.561     1648238.579      567933.248
     1648179.551      567885.505      1648010.28      567862.936
#Sta/Elev= 30
       0  737.89      45  732.23    72.4  728.35    78.2  728.64    86.1   728.2
      90  728.35      98  727.18     104  725.81     108   725.7     114  726.06
     122  725.44     126  724.66     128  723.87   134.6  720.21     136  719.52
     138     719   149.6  719.55     150  719.58     152  720.95     156  725.16
     158  726.04   169.9  729.52   177.8  729.69   203.6  729.42   225.5  730.01
     293  733.56     297  733.87   302.9  734.99   308.9  734.75   334.7  735.83
#Mann= 3 , 0 , 0
       0      .1       0   134.6    .045       0   149.6      .1       0
Bank Sta=134.6,149.6
XS Rating Curve= 0 ,0
Exp/Cntr=0.3,0.1

Type RM Length L Ch R = 1 ,1865.6  ,343.3,340,336.4
XS GIS Cut Line= 4
     1648357.503      567776.998     1648303.683      567775.262
     1648259.412      567746.616     1648086.669        567673.7
#Sta/Elev= 30
       0  746.77       6   743.5      16  737.39      18  736.38    19.9  735.65
    25.9  734.42    35.9  732.02    41.9  730.12    61.7  724.95    77.3  720.44
    82.2  719.34      87  717.56      89  717.24    98.8  717.41   100.7  718.74
   102.7  720.42   104.6  722.51   106.6  725.38   108.6  727.06   112.6  726.78
   116.6  727.14   130.5  727.26   156.4  726.71   166.4  727.15   200.3  727.64
   220.3  728.31   254.2  728.49   280.1   728.9   284.1  729.15   294.1  729.33
#Mann= 3 , 0 , 0
       0      .1       0    82.2    .045       0   100.7      .1       0
Bank Sta=82.2,100.7
XS Rating Curve= 0 ,0
Exp/Cntr=0.3,0.1

Type RM Length L Ch R = 1 ,1525.6  ,344.3,336.4,328.7
XS GIS Cut Line= 4
     1648415.662      567451.477     1648354.899      567439.325
     1648305.419      567418.491     1648152.642      567349.047
#Sta/Elev= 30
       0  744.26      10  738.93      12  737.99      22  734.44      40  729.05
      48   727.1      52  725.77      58  724.05    67.9  720.41    77.9  717.46
    83.8  716.03    85.8  715.37    87.7  714.53    89.8  713.55    91.8   712.9
    93.8   712.7   103.7  713.32   105.7  714.14   107.7  717.22   109.7  719.87
   111.7   720.5   123.6  720.82   135.6  720.91   149.6   721.5   163.6  721.72
   191.6  722.64   229.5  723.07   251.5  722.85   265.5  723.18   283.5  723.18
#Mann= 3 , 0 , 0
       0      .1       0    87.7    .045       0   105.7     .08       0
Bank Sta=87.7,105.7
XS Rating Curve= 0 ,0
Exp/Cntr=0.3,0.1

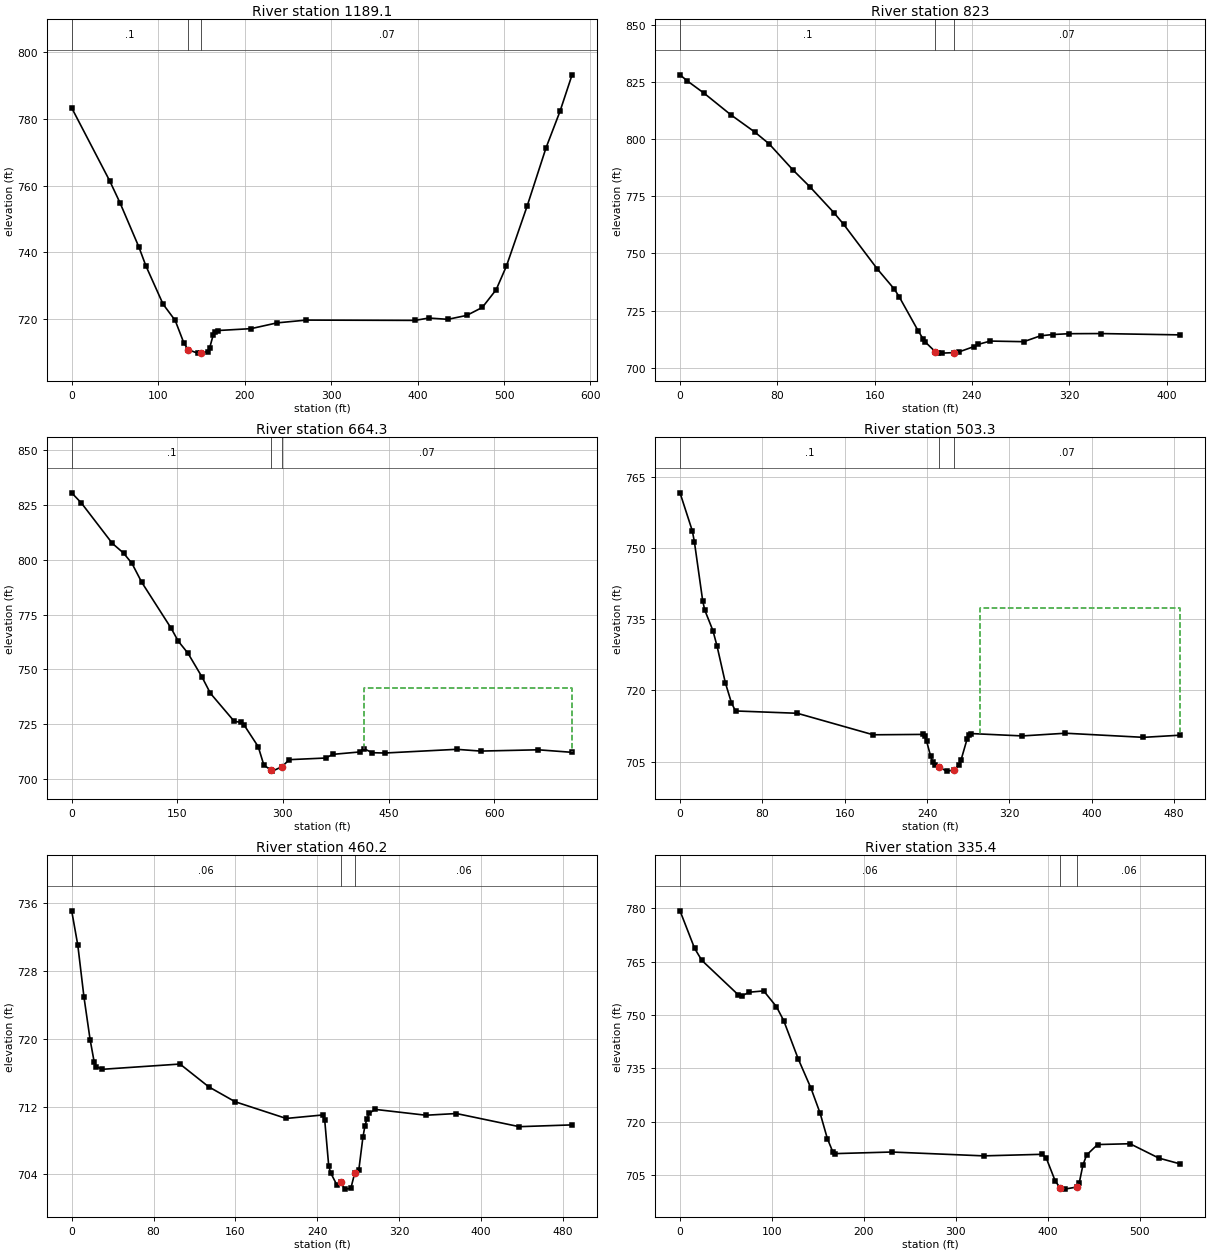
Type RM Length L Ch R = 1 ,1189.1  ,366.2,366.2,365.8
XS GIS Cut Line= 3
     1648532.561      567156.338     1648440.547      567104.255
     1647968.324      567078.213
#Sta/Elev= 30
       0  783.34    43.9  761.43    55.9  754.79    77.8  741.46    85.8  735.86
   105.7  724.33   119.7  719.45   129.7  712.69   134.6  710.65   145.6  709.62
   149.6  709.64   157.6   710.1   159.6  711.23   163.6     715   165.6   715.9
   169.6  716.42   207.5  716.98   237.4  718.71   271.4  719.55   397.1  719.46
     413  720.17     435  719.78   456.9  720.96   474.9  723.36   490.9  728.68
   502.8  735.79   526.8  753.87   548.7  771.42   564.7  782.27   578.7  793.27
#Mann= 3 , 0 , 0
       0      .1       0   134.6    .045       0   149.6     .07       0
Bank Sta=134.6,149.6
XS Rating Curve= 0 ,0
Exp/Cntr=0.3,0.1

Type RM Length L Ch R = 1 ,823     ,159.3,158.6,157.6
XS GIS Cut Line= 4
     1648720.061      566859.463     1648567.283      566763.977
     1648449.096      566759.893     1648336.249      566764.233
#Sta/Elev= 30
       0  828.06     5.9  825.43    19.8  820.02    41.6  810.67    61.4  803.09
    73.2  797.93      93  786.42   106.9  779.08   126.7  767.73   134.6   762.7
   162.3  743.18   176.2  734.44   180.2  731.09   195.9  716.11   199.9  712.68
   201.8  711.25     210  707.02   211.7  706.57   215.6  706.47     225  706.69
   229.4  707.01   241.3  709.26   245.2   710.3   255.1  711.74   282.6  711.47
   296.4  714.04   306.3  714.59   320.2  714.96     346  715.02   411.4  714.44
#Mann= 3 , 0 , 0
       0      .1       0     210    .045       0     225     .07       0
Bank Sta=210,225
XS Rating Curve= 0 ,0
Exp/Cntr=0.3,0.1

Type RM Length L Ch R = 1 ,664.3   ,157.9,161,164.5
XS GIS Cut Line= 3
     1648803.481      566741.799     1648626.397      566606.382
     1648138.772      566608.031
#Sta/Elev= 30
       0  830.45    13.9  825.76    57.7  807.44    73.6  803.03    85.6  798.31
    99.5   789.7   141.3  768.75   151.3  762.92   165.2  757.37   185.1  746.56
     197  739.16   230.9  726.37   240.9  725.94   244.9  724.68   264.9  714.86
   272.9  706.49   283.6  704.03   284.9  703.72   298.6  705.71   308.9  708.94
   360.8  709.69   370.8  711.36   408.8  712.44   414.8     714   426.8   712.1
   444.8  711.97   546.7  713.65   580.6  712.85   662.6  713.43   710.6  712.28
#Mann= 3 , 0 , 0
       0      .1       0   283.6    .045       0   298.6     .07       0
#XS Ineff= 2 , 0
                          415.23          741.43
Permanent Ineff=
       F       F
Bank Sta=283.6,298.6
XS Rating Curve= 0 ,0
Exp/Cntr=0.3,0.1

Type RM Length L Ch R = 1 ,503.3   ,43.1,43.1,41.8
XS GIS Cut Line= 5
     1648819.019      566536.547     1648707.908      566461.894
     1648610.686      566451.477     1648562.074      566444.533
     1648356.871      566445.271
#Sta/Elev= 30
       0  761.71      12  753.65      14  751.32      22  738.97      24  736.98
      32  732.61      36  729.33      44  721.64      50  717.36    53.9  715.67
   113.9  715.18   187.7  710.64   235.6  710.72   237.5  710.41   239.5   709.3
   243.4  706.12   245.4  704.99   247.4  704.28   251.1  703.85   259.1  702.97
   266.1  703.18   270.9  704.23   272.9  705.28   278.8  709.72   280.7   710.7
   282.7   710.9   332.5   710.4   374.4  710.97   450.1   710.1     486  710.56
#Mann= 3 , 0 , 0
       0      .1       0   251.1    .045       0   266.1     .07       0
#XS Ineff= 2 , 0
                          291.23          737.41
Permanent Ineff=
       F       F
Bank Sta=251.1,266.1
XS Rating Curve= 0 ,0
Exp/Cntr=0.3,0.1

Type RM Length L Ch R = 1 ,460.2   ,122.4,124.7,128.4
XS GIS Cut Line= 5
      1648832.04       566494.88     1648720.929      566420.227
     1648623.706      566409.811     1648575.095      566402.866
     1648366.637      566407.293
#Sta/Elev= 30
       0  735.09       6  731.02      12  724.92      18   719.9      22  717.25
      24   716.7      30  716.39   105.9  717.01   133.9  714.33   159.8  712.56
   209.7  710.59   245.4     711   247.4  710.36   251.3  704.97   253.2  704.17
   259.1  702.78   263.1  703.04     267  702.25   272.9  702.33   276.8   704.2
   280.7  704.51   284.7  708.35   286.7  709.72   288.7  710.54   290.7  711.18
   296.6  711.66   346.3  710.97   376.1  711.17   437.6  709.62   489.2  709.83
#Mann= 3 , 0 , 0
       0     .06       0   263.1    .045       0   276.8     .06       0
Bank Sta=263.1,276.8
XS Rating Curve= 0 ,0
Exp/Cntr=0.3,0.1

Type RM Length L Ch R = 1 ,335.4   ,104.5,85.6,67.6
XS GIS Cut Line= 4
     1648985.338      566452.519     1648863.593      566345.397
     1648584.297      566275.436     1648490.329      566278.122
#Sta/Elev= 30
       0  779.27    15.8  768.76    23.7  765.35    63.3  755.67    67.2  755.36
    75.2  756.39      91  756.76   104.8  752.35   112.7  748.44   128.5  737.67
   142.4  729.41   152.3  722.42   160.2  715.26   166.2  711.47   168.2  711.02
   230.2  711.47   330.1  710.39   394.1  710.83   398.1  709.88   408.1  703.25
   413.4  701.42   418.1  701.04   432.1  701.65   434.1  702.78   438.1  707.79
   442.1  710.62     454  713.57   489.3   713.8   520.6  709.77   544.1  708.11
#Mann= 3 , 0 , 0
       0     .06       0   413.4    .045       0   432.1     .06       0
Bank Sta=413.4,432.1
XS Rating Curve= 0 ,0
Exp/Cntr=0.3,0.1

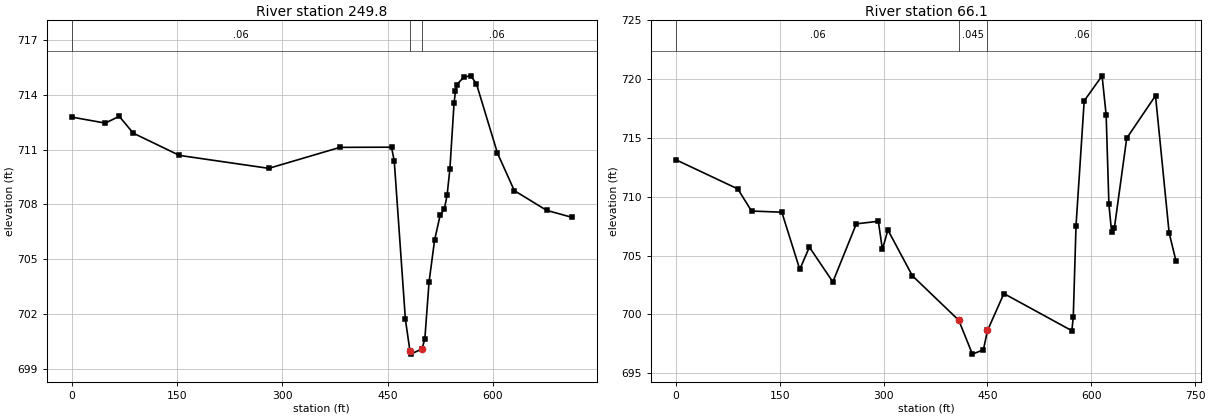
Type RM Length L Ch R = 1 ,249.8   ,166.5,183.7,200
XS GIS Cut Line= 6
     1649107.734      566093.144     1648896.797      566145.227
     1648782.213      566155.644     1648722.318      566158.248
     1648587.985      566221.699     1648416.544      566213.018
#Sta/Elev= 30
       0  712.79    47.8  712.46    67.8  712.83    87.7  711.91   153.5  710.69
   280.8  709.98   382.3  711.13   455.7  711.14   459.6  710.39   475.5   701.7
     482  699.97   483.4   699.8   499.2  700.09   503.2  700.64   509.2  703.75
   517.1  706.05     525  707.41   530.9  707.74   534.9   708.5   538.9  709.95
   544.8  713.54   546.8   714.2   548.8  714.57   558.8  714.98   568.8  715.05
   576.8   714.6   606.7  710.81   630.7  708.76   676.6  707.68   712.5   707.3
#Mann= 3 , 0 , 0
       0     .06       0     482    .045       0   499.2     .06       0
Bank Sta=482,499.2
XS Rating Curve= 0 ,0
Exp/Cntr=0.3,0.1

Type RM Length L Ch R = 1 ,66.1    ,66.9,66.1,65.3
XS GIS Cut Line= 6
     1649071.276      565983.769      1648948.88      566030.644
     1648790.026      566043.665     1648596.244      566007.121
      1648526.57      565975.748     1648420.885       566093.66
#Sta/Elev= 30
       0  713.15    89.4  710.67   109.2  708.79     153  708.69   178.9  703.83
   192.8  705.72   226.7  702.76   260.6   707.7   292.4  707.92   298.3  705.52
   306.2  707.18   341.5  703.29   408.6   699.5   428.3  696.62   444.2  696.99
   450.1  698.63   473.8  701.77     572  698.61     574  699.78     578  707.55
   589.8  718.16   615.6  720.29   621.5  716.97   625.5  709.35   629.4  706.99
   633.4  707.35   651.2  714.98   692.8   718.6   712.5  706.93   722.4  704.54
#Mann= 3 , 0 , 0
       0     .06       0   408.6    .045       0   450.1     .06       0
Bank Sta=408.6,450.1
XS Rating Curve= 0 ,0
Exp/Cntr=0.3,0.1

Chan Stop Cuts=-1
Use User Specified Reach Order=0
Composite Channel Slope=5